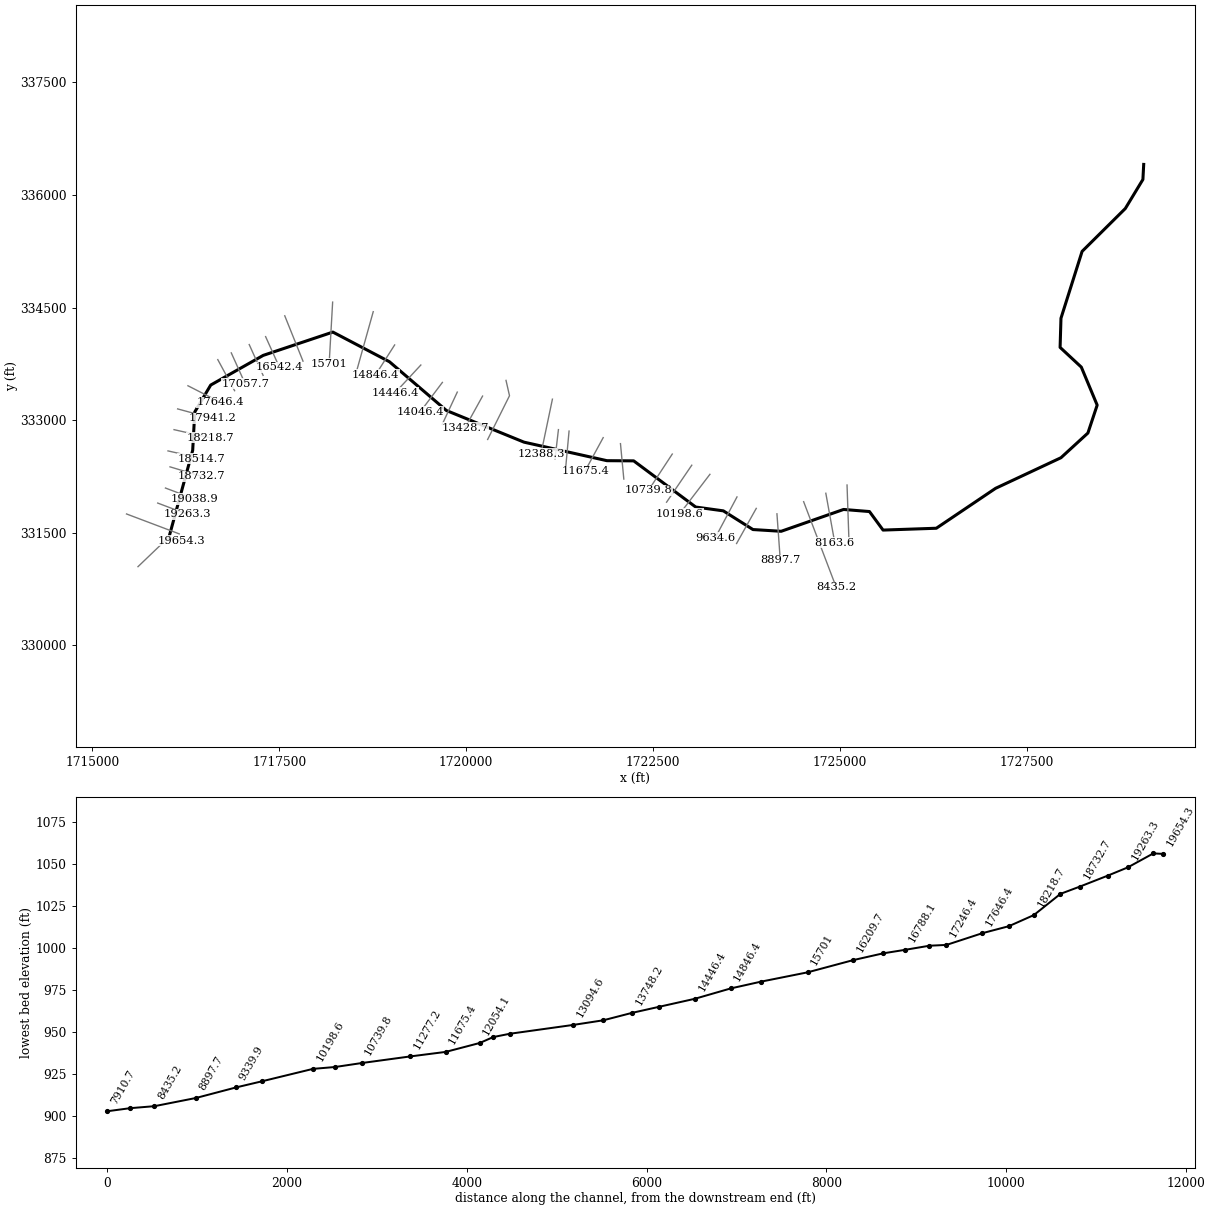
--- BEECHCRK.prj (project) ---

Proj Title=BEECHCRK
Current Plan=p01
Default Exp/Contr=0,0
English Units
Geom File=g01
Flow File=f01
Plan File=p01
BEGIN DESCRIPTION:
END DESCRIPTION:
DSS Export Rating Curves= 0
DSS Export Rating Curve Sorted= 0
DSS Export Volume Flow Curves= 0
DXF OffsetX= 0
DXF OffsetY= 0
DXF ScaleX= 0
DXF ScaleY= 0

--- BEECHCRK.p01 (plan) ---

Plan Title=Floodplain
Program Version=4.00
Geom File=g01
Flow File=f01
K Sum by GR=0
Std Step Tol=0.01
Critical Tol=0.01
Num of Std Step Trials=20
Max Error Tol=0.3
Flow Tol Ratio=0.001
Split Flow NTrial=30
Split Flow Tol=0.02
Split Flow Ratio=0.02
Log Output Level=0
Friction Slope Method=1
Unsteady Friction Slope Method=2
Unsteady Bridges Friction Slope Method=1
Global Log Level=0
CheckData=False
Run HTab=0
Run UNet=0
Run PostProcess=0
UNET Theta=0
UNET Theta Warmup=0
UNET ZTol=0
UNET ZSATol=0
UNET MxIter=0
UNET MaxInSteps=0
UNET DtIC=0
UNET DtMin=0
UNET MaxCRTS=0
UNET WFStab=0
UNET SFStab=0
UNET WFX=0
UNET SFX=0
UNET DSS MLevel=0
UNET DZMax Abort=0
UNET Convert EG Bridges=0
UNET Use Existing IB Tables=0
UNET Froude Limit=0
UNET Froude Power=0
Write IC File=0
Echo Input=False
Echo Output=False
Write Detailed=0

--- BEECHCRK.f01 (steady flow) ---

Flow Title=NFF Regression Equation
Program Version=4.00
Number of Profiles=1
Profile Names=P100yr
River Rch & RM=BEECHCRK,Main      ,19654.3
708.8457
River Rch & RM=BEECHCRK,Main      ,19263.3
712.1829
River Rch & RM=BEECHCRK,Main      ,19038.9
996.4043
River Rch & RM=BEECHCRK,Main      ,18514.7
1010.524
River Rch & RM=BEECHCRK,Main      ,18218.7
1157.460
River Rch & RM=BEECHCRK,Main      ,17646.4
1167.979
River Rch & RM=BEECHCRK,Main      ,15180.7
1295.857
River Rch & RM=BEECHCRK,Main      ,12388.3
1389.082
River Rch & RM=BEECHCRK,Main      ,10739.8
1530.441
River Rch & RM=BEECHCRK,Main      ,8435.2
1674.569
River Rch & RM=BEECHCRK,Main      ,8163.6
2162.046
River Rch & RM=BEECHCRK,Main      ,4448.5
2266.046
River Rch & RM=BEECHCRK,Main      ,65.5
2514.752
Boundary for River Rch & Prof#=BEECHCRK,Main      ,1
Up Type=0
Dn Type=3
Dn Slope=0.010759

--- BEECHCRK.g01 (geometry) ---

Geom Title=USGS 10m DEM
Program Version=4.10

River Reach=BEECHCRK        ,Main
Reach XY= 30
     1716021.165      331425.997     1716342.373      332598.099
      1716370.17      333109.252     1716583.279      333467.523
     1717285.536      333862.857     1718216.731      334173.255
     1718973.038      333778.308     1719735.136      333128.556
     1720772.886       332706.97     1721881.286      332460.273
     1722239.171      332457.956     1723068.444       331842.95
     1723437.911       331791.99     1723834.017      331542.976
     1724211.591      331519.812     1725045.497      331810.521
       1725391.8      331782.724     1725573.638      331536.027
     1726285.933      331560.349     1727078.144      332091.964
     1727952.587      332499.652     1728312.788      332828.581
     1728436.716      333200.364     1728224.765      333706.499
     1727941.005      333969.411     1727952.587      334357.409
     1728235.188      335248.068     1728813.132      335819.062
     1729048.247      336205.902     1729058.898      336406.469

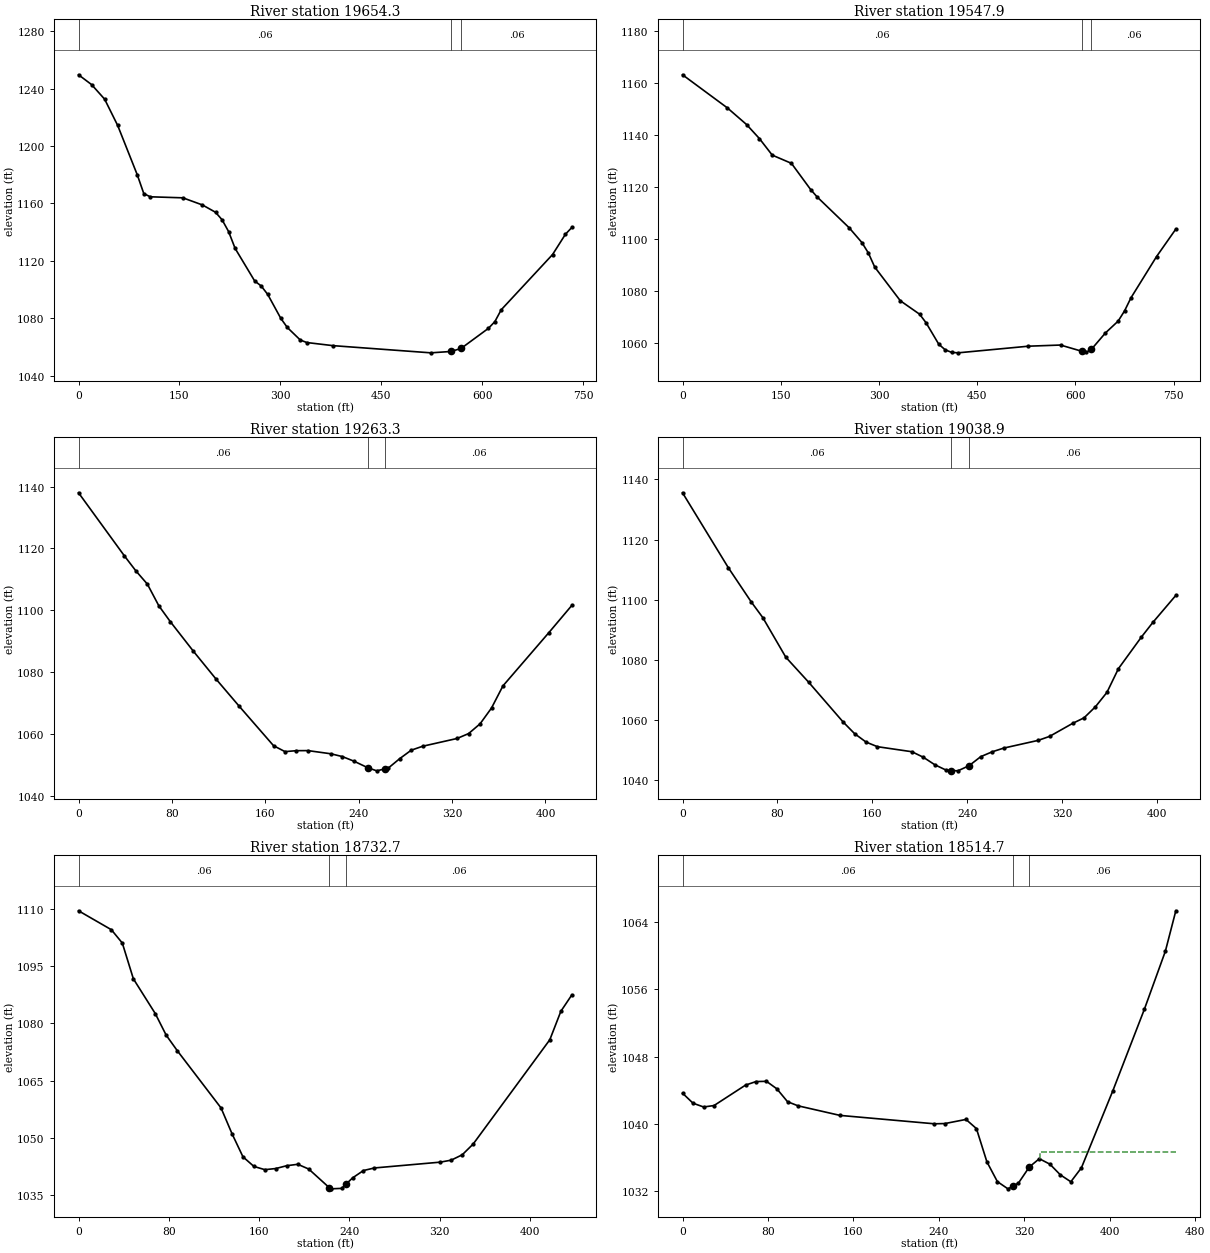
Type RM Length L Ch R = 1 ,19654.3 ,124.6,106.4,94.3
XS GIS Cut Line= 4
     1715611.015      331048.742     1716003.895      331423.494
      1716040.18      331433.148     1716187.317      331392.516
#Sta/Elev= 30
       0 1249.55    19.4 1242.72    38.8 1232.58    58.2 1214.28    87.3 1179.95
      97 1166.88   106.6 1164.64   155.1 1163.92   184.2 1158.95   203.6 1153.88
   213.3 1148.68     223 1140.48   232.7 1128.74   261.8 1106.05   271.5 1102.57
   281.2 1096.68   300.6 1080.05   310.3 1073.69   329.6 1064.96   339.3 1063.22
   378.1 1061.06   523.6 1056.05   553.4    1057   568.4 1059.08   609.1 1073.08
   618.7 1077.75   628.2 1086.03   704.5 1124.47   723.6 1138.57   733.1 1143.29
#Mann= 3 , 0 , 0
       0     .06       0   553.4    .045       0   568.4     .06       0
Bank Sta=553.4,568.4
XS Rating Curve= 0 ,0
Exp/Cntr=0.3,0.1

Type RM Length L Ch R = 1 ,19547.9 ,284.6,284.6,284.5
XS GIS Cut Line= 2
     1715457.613      331750.591     1716162.619      331485.245
#Sta/Elev= 30
       0 1163.34    68.5 1150.59    97.8 1144.19   117.4 1138.79     137 1132.42
   166.3 1129.26   195.7 1119.16   205.4 1116.37   254.4 1104.48   273.9 1098.78
   283.7  1094.8   293.5 1089.34   332.6 1076.37     362  1071.2   371.8 1067.94
   391.3 1059.65   401.1  1057.5   410.9 1056.51   420.7 1056.33   528.3 1058.89
   577.2 1059.33   609.3 1056.97   616.3 1056.49   624.3 1057.66   645.7 1063.96
   665.2 1068.54     675 1072.47   684.8 1077.51   723.9  1093.4   753.3 1103.96
#Mann= 3 , 0 , 0
       0     .06       0   609.3    .045       0   624.3     .06       0
#XS Ineff= 2 , 0
          547.27 1059.06
Permanent Ineff=
       F       F
Bank Sta=609.3,624.3
XS Rating Curve= 0 ,0
Exp/Cntr=0.3,0.1

Type RM Length L Ch R = 1 ,19263.3 ,224.4,224.5,224.5
XS GIS Cut Line= 2
     1715874.578      331895.777     1716270.111      331746.909
#Sta/Elev= 30
       0 1138.03    39.3  1117.6    49.1 1112.76      59 1108.45    68.8 1101.44
    78.6 1096.32    98.3 1086.78   117.9 1077.67   137.6 1068.94   167.1 1056.13
   176.9 1054.22   186.7 1054.53   196.6 1054.55   216.2 1053.52     226 1052.62
   235.9 1051.14   247.8 1049.01   255.5    1048   262.8 1048.67   265.4  1048.9
   275.2 1051.96     285 1054.68   294.8 1055.96   324.3 1058.48   334.2 1060.07
     344 1063.22   353.8 1068.34   363.6 1075.51     403 1092.78   422.6 1101.56
#Mann= 3 , 0 , 0
       0     .06       0   247.8    .045       0   262.8     .06       0
Bank Sta=247.8,262.8
XS Rating Curve= 0 ,0
Exp/Cntr=0.3,0.1

Type RM Length L Ch R = 1 ,19038.9 ,304.6,306.2,307.7
XS GIS Cut Line= 2
     1715978.299       332095.95     1716367.585      331949.433
#Sta/Elev= 30
       0 1135.55    38.7 1110.58      58 1099.22    67.7 1094.03    87.1 1080.86
   106.4 1072.53   135.4 1059.33   145.1 1055.44   154.8 1052.63   164.4  1051.1
   193.5 1049.42   203.1 1047.58   212.8 1045.08   222.5 1043.27   226.6 1043.18
   232.2 1043.07   241.6 1044.77   251.5 1047.79   261.2 1049.41   270.8 1050.63
   299.9  1053.2   309.5 1054.52   328.9 1058.84   338.6  1060.7   348.2 1064.38
   357.9 1069.16   367.6 1077.06   386.9 1087.53   396.6 1092.42     416 1101.42
#Mann= 3 , 0 , 0
       0     .06       0   226.6    .045       0   241.6     .06       0
Bank Sta=226.6,241.6
XS Rating Curve= 0 ,0
Exp/Cntr=0.3,0.1

Type RM Length L Ch R = 1 ,18732.7 ,216.4,218,219.6
XS GIS Cut Line= 2
     1716038.928      332378.195     1716457.659      332252.886
#Sta/Elev= 30
       0 1109.48    29.1 1104.52    38.8 1101.03    48.6 1091.66      68 1082.56
    77.7 1076.89    87.4 1072.88   126.3 1057.83     136 1051.09   145.7 1045.04
   155.4 1042.52   165.1 1041.67   174.8 1041.97   184.5 1042.71   194.3 1043.08
     204 1041.83   222.3 1036.93   223.4 1036.65   233.1 1036.77   237.3 1037.95
   242.8 1039.51   252.5 1041.45   262.2 1042.12   320.5 1043.64   330.2 1044.16
     340 1045.57   349.7 1048.39   417.6  1075.7   427.4 1083.16   437.1 1087.44
#Mann= 3 , 0 , 0
       0     .06       0   222.3    .045       0   237.3     .06       0
Bank Sta=222.3,237.3
XS Rating Curve= 0 ,0
Exp/Cntr=0.3,0.1

Type RM Length L Ch R = 1 ,18514.7 ,296.1,296,296
XS GIS Cut Line= 2
     1716012.026      332590.512     1716462.644      332489.019
#Sta/Elev= 30
       0 1043.65     9.8 1042.46    19.7 1042.01    29.5 1042.18      59 1044.61
    68.8 1045.03    78.6 1045.06    88.4 1044.16    98.3 1042.64   108.1 1042.15
   147.4 1041.01   235.9 1040.01   245.7 1040.04   265.4 1040.53   275.2 1039.44
     285 1035.49   294.8 1033.14   304.7 1032.28   309.8 1032.63   314.5 1032.96
   324.8 1034.89   334.1 1035.86     344 1035.21   353.8 1033.94   363.6 1033.12
   373.5 1034.78   402.9 1043.93   432.4 1053.61   452.1 1060.52   461.9 1065.33
#Mann= 3 , 0 , 0
       0     .06       0   309.8    .045       0   324.8     .06       0
#XS Ineff= 2 , 0
                          334.75          1036.7
Permanent Ineff=
       F       F
Bank Sta=309.8,324.8
XS Rating Curve= 0 ,0
Exp/Cntr=0.3,0.1

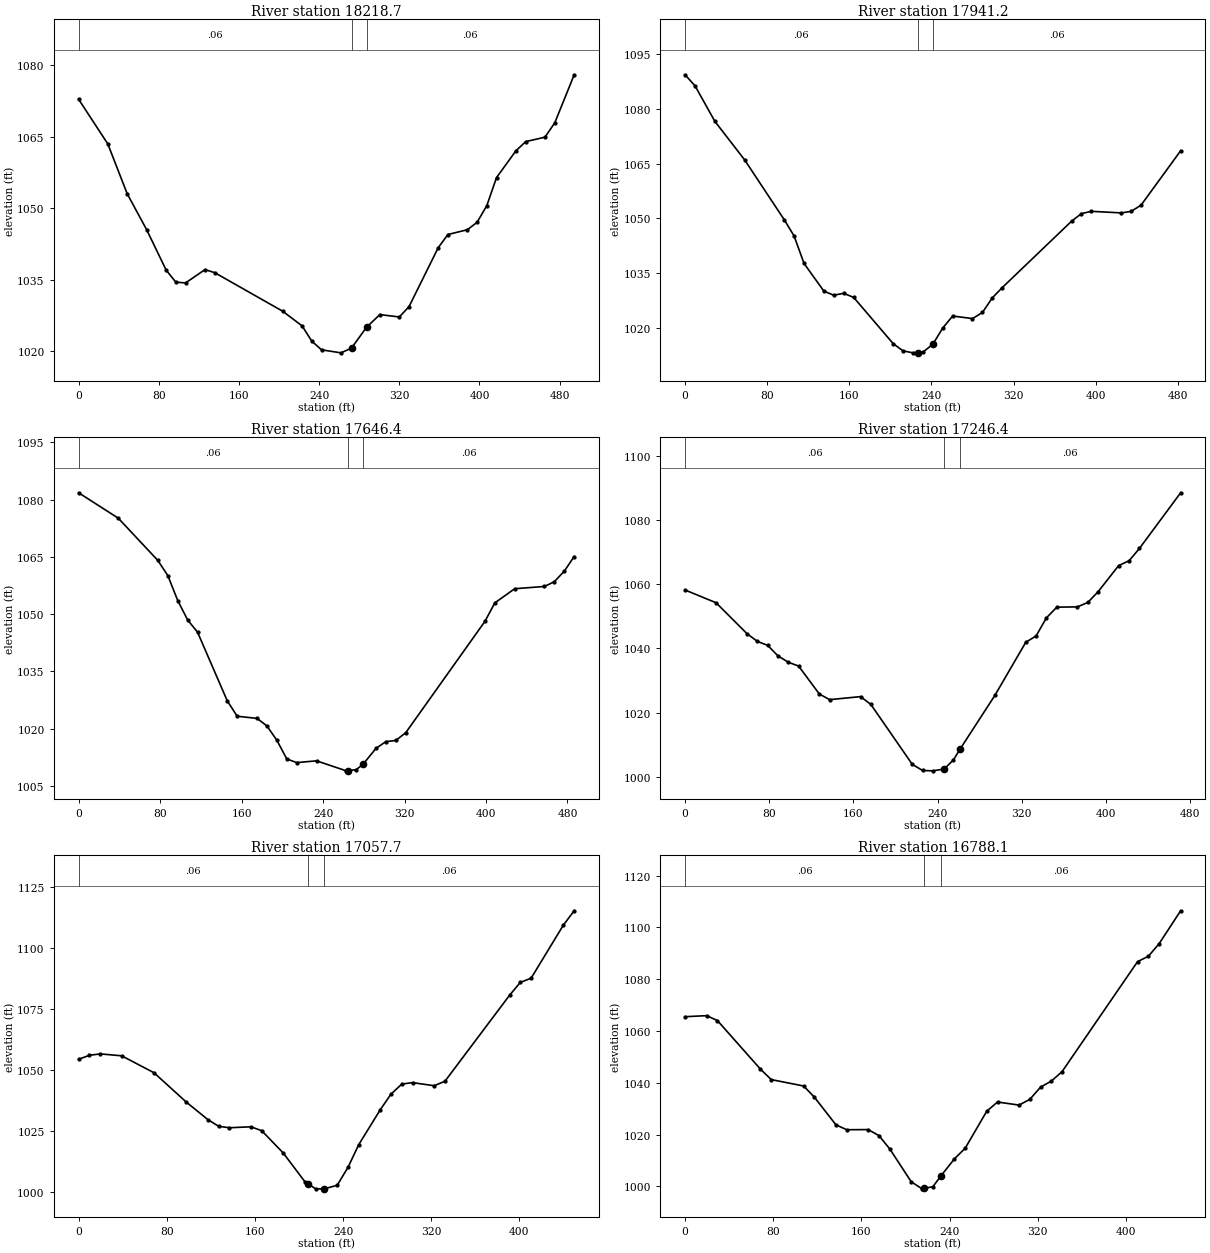
Type RM Length L Ch R = 1 ,18218.7 ,278.4,277.5,276.6
XS GIS Cut Line= 2
     1716092.999      332873.536     1716575.456      332764.872
#Sta/Elev= 30
       0 1072.83    29.1 1063.48    48.5 1053.01    67.9 1045.48    87.3 1037.03
      97 1034.49   106.7 1034.33   126.1 1037.12   135.8 1036.48   203.6  1028.4
     223 1025.32   232.7 1022.11   242.4  1020.3   261.8 1019.67   272.3 1020.66
   287.3 1025.04   300.6 1027.69     320 1027.19   329.7 1029.36   358.8  1041.7
   368.5 1044.48   387.9 1045.48   397.6 1047.03   407.3 1050.52     417 1056.41
   436.4 1062.04   446.1 1063.95   465.4 1064.89   475.2 1067.92   494.5 1077.97
#Mann= 3 , 0 , 0
       0     .06       0   272.3    .045       0   287.3     .06       0
Bank Sta=272.3,287.3
XS Rating Curve= 0 ,0
Exp/Cntr=0.3,0.1

Type RM Length L Ch R = 1 ,17941.2 ,299.6,294.8,290
XS GIS Cut Line= 2
     1716141.083      333149.907     1716607.236      333024.197
#Sta/Elev= 30
       0 1089.43     9.7 1086.38      29 1076.64    57.9  1066.1    96.6 1049.62
   106.2 1045.16   115.9 1037.61   135.2 1030.02   144.8  1028.9   154.5 1029.41
   164.2  1028.3   202.8 1015.58   212.4  1013.6   222.1 1013.07   226.5 1013.16
   231.8 1013.27   241.5 1015.48   251.1 1019.91   260.7 1023.18     280 1022.48
   289.7 1024.15   299.3 1028.17     309 1030.99   376.6 1049.24   386.2 1051.31
   395.9 1051.93   424.9  1051.5   434.5 1051.91   444.2 1053.61   482.8 1068.56
#Mann= 3 , 0 , 0
       0     .06       0   226.5    .045       0   241.5     .06       0
Bank Sta=226.5,241.5
XS Rating Curve= 0 ,0
Exp/Cntr=0.3,0.1

Type RM Length L Ch R = 1 ,17646.4 ,413.6,400,386.4
XS GIS Cut Line= 2
     1716278.911      333458.285     1716712.608      333237.662
#Sta/Elev= 30
       0 1081.78    38.9 1075.13    77.8 1064.05    87.6 1060.07    97.3 1053.55
     107 1048.48   116.8 1045.23     146 1027.23   155.7 1023.23   175.2 1022.66
   184.9 1020.68   194.6 1016.96   204.4 1012.04   214.1 1011.08   233.6 1011.54
   262.8 1008.92   264.3 1008.97   272.5 1009.22   279.3 1010.64     292 1014.81
   301.7 1016.58   311.4 1016.87   321.2 1018.91     399  1048.1   408.7 1052.93
   428.2 1056.64   457.4 1057.23   467.1 1058.48   476.9 1061.24   486.6 1065.08
#Mann= 3 , 0 , 0
       0     .06       0   264.3    .045       0   279.3     .06       0
Bank Sta=264.3,279.3
XS Rating Curve= 0 ,0
Exp/Cntr=0.3,0.1

Type RM Length L Ch R = 1 ,17246.4 ,190.3,188.7,187
XS GIS Cut Line= 2
     1716677.956      333806.469     1716902.754      333392.555
#Sta/Elev= 30
       0 1058.18    29.4 1054.23    58.9 1044.58    68.7  1042.2    78.5 1040.96
    88.3 1037.68    98.1 1035.71   107.9 1034.52   127.6 1025.82   137.4 1024.08
   166.8 1025.02   176.6 1022.57   215.9 1003.96   225.7 1002.04   235.5 1001.93
   246.2 1002.48   255.1 1005.35   261.2 1008.61   294.4 1025.38   323.8 1041.92
   333.6 1043.89   343.4 1049.51   353.3 1052.85   372.9 1052.93   382.7  1054.3
   392.5 1057.63   412.1 1065.79     422 1067.28   431.8  1071.1     471 1088.43
#Mann= 3 , 0 , 0
       0     .06       0   246.2    .045       0   261.2     .06       0
Bank Sta=246.2,261.2
XS Rating Curve= 0 ,0
Exp/Cntr=0.3,0.1

Type RM Length L Ch R = 1 ,17057.7 ,269.7,269.7,269.6
XS GIS Cut Line= 2
     1716858.388      333896.226     1717043.767      333486.401
#Sta/Elev= 30
       0 1054.53     9.8 1056.15    19.6 1056.73    39.1 1055.94    68.4 1049.01
    97.8 1036.96   117.3 1029.82   127.1 1027.07   136.9 1026.48   156.4 1026.87
   166.2 1025.27   185.8  1016.1   205.3 1004.41     208 1003.62   215.1 1001.48
     223 1001.46   234.7 1002.92   244.5 1010.26   254.2 1019.52   273.8 1033.86
   283.6  1040.3   293.4 1044.37   303.1 1044.96   322.7 1043.69   332.5 1045.52
   391.1 1080.71   400.9    1086   410.7 1087.72     440 1109.48   449.8 1115.34
#Mann= 3 , 0 , 0
       0     .06       0     208    .045       0     223     .06       0
Bank Sta=208,223
XS Rating Curve= 0 ,0
Exp/Cntr=0.3,0.1

Type RM Length L Ch R = 1 ,16788.1 ,245.6,245.7,245.8
XS GIS Cut Line= 2
     1717098.231      334006.984      1717283.61      333597.159
#Sta/Elev= 30
       0 1065.52    19.6 1065.93    29.3 1064.04    68.4 1045.27    78.2 1041.23
   107.6 1038.75   117.3 1034.46   136.9 1023.76   146.7 1021.86   166.2 1021.92
     176 1019.58   185.8 1014.43   205.3 1001.74   215.1  999.03   217.1   999.2
   224.9  999.86   232.1 1003.95   244.5 1010.65   254.2 1014.69   273.8 1029.02
   283.6 1032.57   303.1 1031.38   312.9 1033.59   322.7 1038.34   332.5 1040.66
   342.2 1044.32   410.7  1086.8   420.5 1088.87   430.2 1093.68   449.8 1106.44
#Mann= 3 , 0 , 0
       0     .06       0   217.1    .045       0   232.1     .06       0
Bank Sta=217.1,232.1
XS Rating Curve= 0 ,0
Exp/Cntr=0.3,0.1

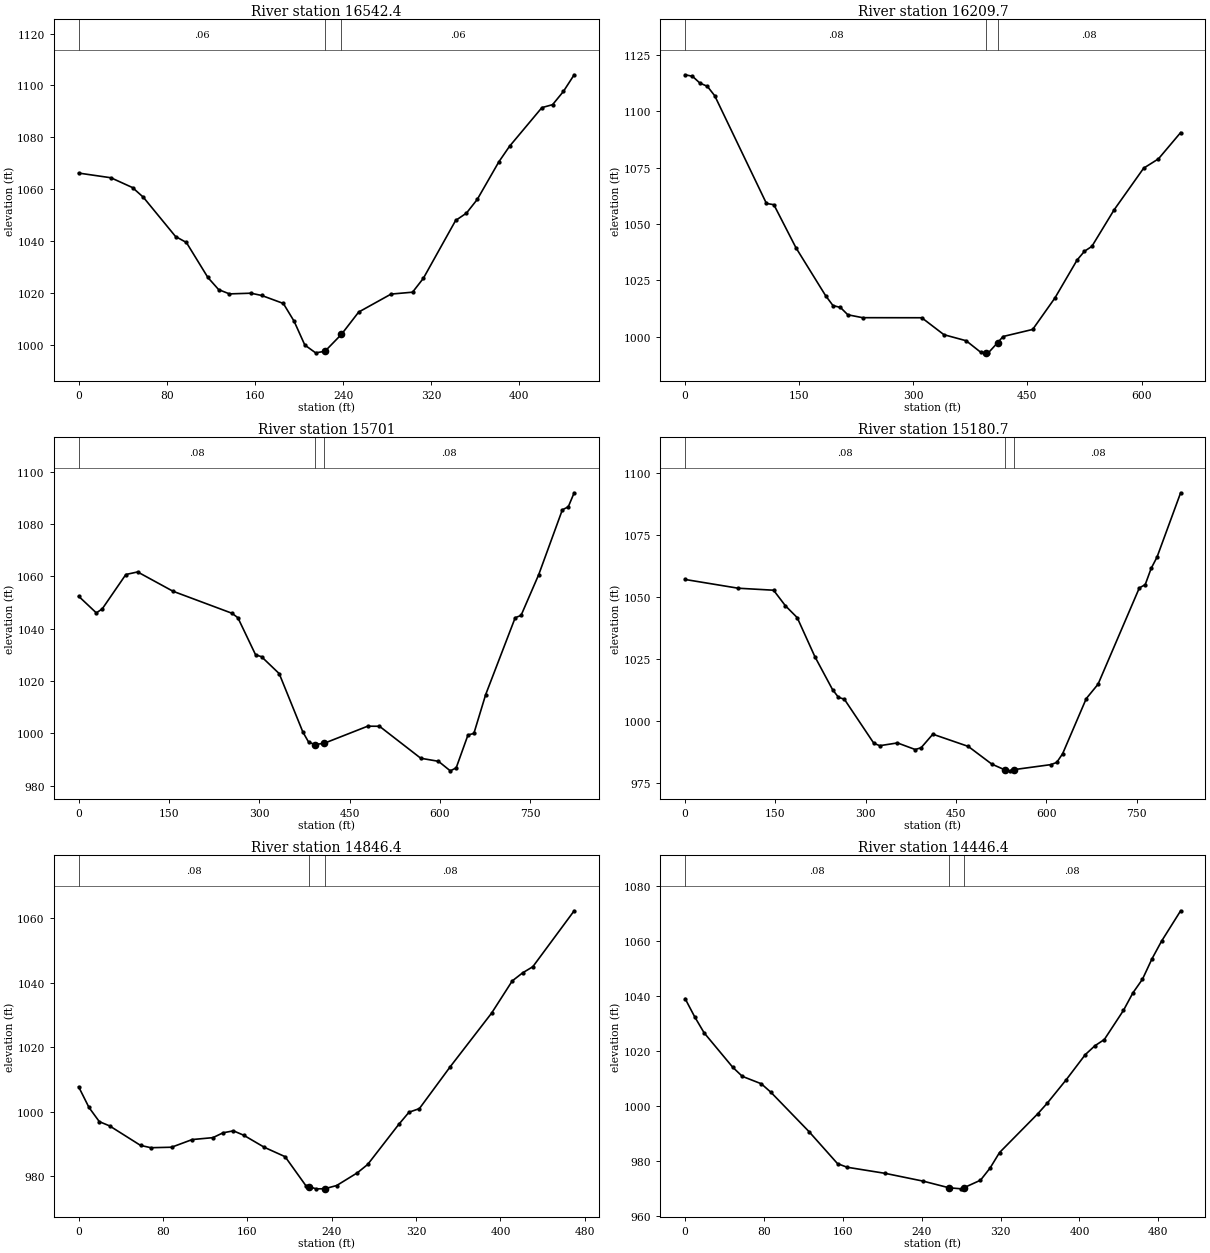
Type RM Length L Ch R = 1 ,16542.4 ,333.6,332.7,331.8
XS GIS Cut Line= 2
     1717317.463      334112.589     1717502.842      333702.764
#Sta/Elev= 30
       0 1066.23    29.3 1064.42    48.9 1060.64    58.7 1056.93      88 1041.76
    97.8 1039.48   117.3 1025.99   127.1  1021.3   136.9 1019.65   156.4 1019.92
   166.2 1019.04   185.8 1015.97   195.6  1009.1   205.3  999.94   215.1  996.93
   223.6  997.53   238.6 1004.08   254.2 1012.65   283.6 1019.58   303.1 1020.31
   312.9 1025.66   342.2 1047.96     352 1050.78   361.8 1056.05   381.4 1070.54
   391.1 1076.54   420.5 1091.46   430.2  1092.6     440 1097.68   449.8 1104.12
#Mann= 3 , 0 , 0
       0     .06       0   223.6    .045       0   238.6     .06       0
Bank Sta=223.6,238.6
XS Rating Curve= 0 ,0
Exp/Cntr=0.3,0.1

Type RM Length L Ch R = 1 ,16209.7 ,518.5,508.7,498.9
XS GIS Cut Line= 2
     1717573.553      334390.032     1717817.253      333785.968
#Sta/Elev= 30
       0 1116.13     9.7 1115.46    19.4 1112.46    29.2 1111.02    38.9 1106.87
   106.9 1059.12   116.7 1058.55   145.8 1039.43   184.7 1018.25   194.4 1013.86
   204.2 1013.02   213.9 1009.78   233.3 1008.49   311.1 1008.46   340.3 1000.94
   369.4  998.28   388.9  993.09   395.7  992.97   398.6  992.91   410.7  997.36
     418 1000.15   456.9 1003.28   486.1  1017.2   515.3 1034.04     525 1037.93
   534.7 1040.08   563.9 1056.25   602.8 1074.75   622.2 1078.86   651.4 1090.52
#Mann= 3 , 0 , 0
       0     .08       0   395.7    .045       0   410.7     .08       0
Bank Sta=395.7,410.7
XS Rating Curve= 0 ,0
Exp/Cntr=0.3,0.1

Type RM Length L Ch R = 1 ,15701   ,525.6,520.2,514.9
XS GIS Cut Line= 2
     1718213.669      334572.315     1718166.985      333750.952
#Sta/Elev= 30
       0 1052.35    29.4 1045.98    39.2 1047.52    78.4 1060.65    97.9 1061.63
   156.7 1054.25   254.6 1045.84   264.4 1044.13   293.8 1029.96   303.6 1029.25
     333 1022.77   372.2  1000.5     382  996.53   392.8  995.68   407.8  996.17
   479.9 1002.69   499.5 1002.66     568  990.44   597.4  989.27     617  985.63
   626.8  986.76   646.4  999.33   656.2  999.93   675.8 1014.78   724.8 1044.15
   734.5 1045.01   763.9 1060.64   803.1 1085.38   812.9 1086.51   822.7 1091.88
#Mann= 3 , 0 , 0
       0     .08       0   392.8    .045       0   407.8     .08       0
#XS Ineff= 2 , 0
                          489.67         1001.99
Permanent Ineff=
       F       F
Bank Sta=392.8,407.8
XS Rating Curve= 0 ,0
Exp/Cntr=0.3,0.1

Type RM Length L Ch R = 1 ,15180.7 ,341,334.3,327.7
XS GIS Cut Line= 2
     1718756.482        334444.8     1718533.866      333652.803
#Sta/Elev= 30
       0 1057.06    88.2 1053.54   146.9 1052.74   166.5 1046.49   186.1 1041.72
   215.5 1025.99   244.8 1012.75   254.6 1009.65   264.4 1008.88   313.4  991.14
   323.2  990.19   352.6   991.3     382  988.65   391.8  989.36   411.3  994.81
   470.1   989.9   509.3  982.76   531.7  980.38   538.7  980.07   546.7  980.58
   607.2  982.57     617  983.46   626.8  986.97     666 1009.13   685.6 1014.93
   754.1 1053.66   763.9 1054.99   773.7 1061.49   783.5 1066.06   822.7 1091.94
#Mann= 3 , 0 , 0
       0     .08       0   531.7    .045       0   546.7     .08       0
Bank Sta=531.7,546.7
XS Rating Curve= 0 ,0
Exp/Cntr=0.3,0.1

Type RM Length L Ch R = 1 ,14846.4 ,404.1,400,395.9
XS GIS Cut Line= 2
     1719042.721      334001.794      1718789.42      333606.011
#Sta/Elev= 30
       0 1007.71     9.8 1001.31    19.6  996.91    29.4  995.58    58.7  989.54
    68.5  988.82    88.1  988.97   107.7  991.35   127.3  991.94     137  993.45
   146.8  994.05   156.6  992.68   176.2  988.93   195.8  986.04   215.4  977.09
   218.3  976.78   225.2  976.07   233.3  976.09   244.7   977.1   264.3  981.04
   274.1  983.63   303.5  996.03   313.3  999.83   323.1 1000.94   352.4 1013.94
   391.6 1030.55   411.2 1040.54     421 1043.03   430.7 1044.94   469.9 1062.28
#Mann= 3 , 0 , 0
       0     .08       0   218.3    .045       0   233.3     .08       0
Bank Sta=218.3,233.3
XS Rating Curve= 0 ,0
Exp/Cntr=0.3,0.1

Type RM Length L Ch R = 1 ,14446.4 ,397.5,400,402.5
XS GIS Cut Line= 2
     1719393.069      333734.549     1719050.424      333366.907
#Sta/Elev= 30
       0 1039.11     9.7  1032.5    19.3 1026.65    48.3 1014.14      58 1010.83
    77.3 1008.12      87 1005.04   125.6  990.75   154.6  979.07   164.3  977.76
     203  975.53   241.6  972.69   267.6  970.29   280.3   969.9   282.6  970.27
   299.6  973.04   309.3  977.45   318.9   983.1   357.6  997.17   367.3 1001.06
   386.6 1009.61   405.9 1018.73   415.6 1021.94   425.2 1024.22   444.6 1034.82
   454.2  1041.2   463.9 1046.17   473.6 1053.63   483.2 1059.98   502.6 1071.06
#Mann= 3 , 0 , 0
       0     .08       0   267.6    .045       0   282.6     .08       0
Bank Sta=267.6,282.6
XS Rating Curve= 0 ,0
Exp/Cntr=0.3,0.1

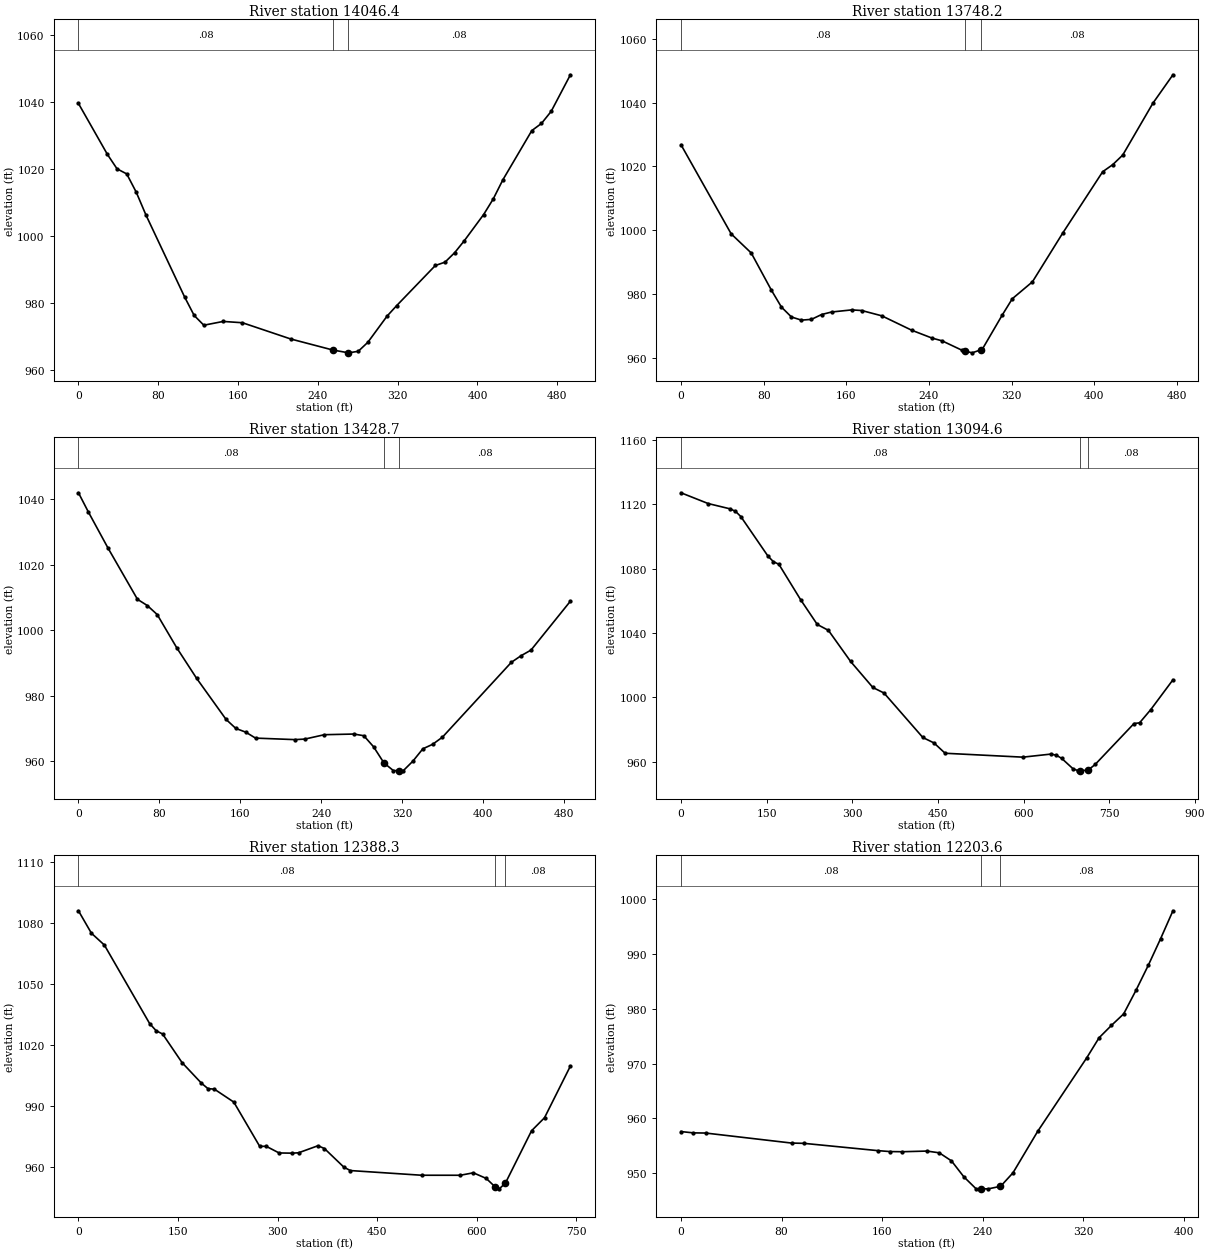
Type RM Length L Ch R = 1 ,14046.4 ,293.7,298.2,302.8
XS GIS Cut Line= 2
     1719681.173       333502.83     1719383.683      333109.434
#Sta/Elev= 30
       0  1039.6      29  1024.4    38.7 1020.07    48.4 1018.56      58 1013.06
    67.7 1006.26   106.4  981.81     116  976.28   125.7  973.36   145.1  974.49
   164.4   974.1   212.8  969.25   254.9  965.96   269.9  965.16   270.8  965.11
   280.5  965.57   290.1  968.25   309.5  976.12   319.1  979.24   357.8   991.2
   367.5   992.2   377.2  995.04   386.8  998.59   406.2 1006.42   415.8 1011.06
   425.5  1016.8   454.5 1031.49   464.2 1033.64   473.9 1037.23   493.2 1048.17
#Mann= 3 , 0 , 0
       0     .08       0   254.9    .045       0   269.9     .08       0
Bank Sta=254.9,269.9
XS Rating Curve= 0 ,0
Exp/Cntr=0.3,0.1

Type RM Length L Ch R = 1 ,13748.2 ,321,319.4,317.9
XS GIS Cut Line= 2
     1719880.273      333373.817     1719678.231      332942.598
#Sta/Elev= 30
       0 1026.83    48.6  998.86      68  992.87    87.5  981.21    97.2  975.91
   106.9  972.79   116.6   971.8   126.3  972.04   136.1  973.56   145.8  974.35
   165.2  975.01   174.9  974.82   194.4  973.15   223.5  968.61     243  966.17
   252.7  965.31   272.1  962.34   275.4  962.07   281.8  961.54   290.4   962.5
   291.6  962.63     311  973.41   320.7  978.51   340.2  983.82   369.3     999
   408.2 1018.36   417.9 1020.57   427.6 1023.58   456.8 1039.85   476.2 1048.77
#Mann= 3 , 0 , 0
       0     .08       0   275.4    .045       0   290.4     .08       0
Bank Sta=275.4,290.4
XS Rating Curve= 0 ,0
Exp/Cntr=0.3,0.1

Type RM Length L Ch R = 1 ,13428.7 ,333.2,334.1,335.1
XS GIS Cut Line= 2
     1720218.553      333320.871     1719982.647      332895.212
#Sta/Elev= 30
       0    1042     9.7  1036.2    29.2 1025.15    58.4 1009.48    68.1 1007.59
    77.9 1004.84    97.3  994.66   116.8  985.41     146  972.84   155.7  970.07
   165.5  968.94   175.2  967.12   214.1  966.66   223.9  966.82   243.3  968.16
   272.5  968.36   282.3  967.85     292  964.46   302.2  959.55   311.5  957.22
   317.2  957.17   321.2  957.13   330.9   960.1   340.7  963.85   350.4  965.23
   360.1  967.41   428.3  990.26     438  992.29   447.7  993.98   486.7 1008.92
#Mann= 3 , 0 , 0
       0     .08       0   302.2    .045       0   317.2     .08       0
Bank Sta=302.2,317.2
XS Rating Curve= 0 ,0
Exp/Cntr=0.3,0.1

Type RM Length L Ch R = 1 ,13094.6 ,700.5,706.3,712.1
XS GIS Cut Line= 3
     1720532.095       333529.76     1720578.608      333325.552
     1720286.587      332742.886
#Sta/Elev= 30
       0  1127.1    47.6 1120.41    85.7 1117.14    95.2 1115.63   104.7 1112.36
   152.3 1087.75   161.8  1084.3   171.4 1082.68   209.4 1060.71   238.6  1045.3
   258.1 1041.64     297  1022.3   335.9 1006.16   355.4 1002.72   423.4  975.09
   442.9  971.71   462.4   965.3   598.5  962.88   647.2  964.77   656.9  964.13
   666.6  962.08   686.1  955.72   695.8  954.38   697.7  954.42   712.7  954.83
     725  958.32   793.1  983.77   802.8   984.2   822.3  992.37   861.2 1010.92
#Mann= 3 , 0 , 0
       0     .08       0   697.7    .045       0   712.7     .08       0
Bank Sta=697.7,712.7
XS Rating Curve= 0 ,0
Exp/Cntr=0.3,0.1

Type RM Length L Ch R = 1 ,12388.3 ,182.7,184.7,186.8
XS GIS Cut Line= 2
     1721152.501      333279.874     1720999.968      332554.744
#Sta/Elev= 30
       0 1086.12    19.5 1075.08      39 1069.25   107.2 1030.57     117 1027.02
   126.8  1025.4     156 1011.34   185.2 1001.19     195  998.51   204.8  998.22
     234  991.86     273  970.06   282.8  970.08   302.2   966.8   321.8   966.7
   331.5  966.88   360.8  970.36   370.5  968.98   399.8   959.8   409.5  958.13
   516.8  955.82   575.2  955.81   594.8  957.02   614.2  954.25     628  949.97
   633.8  949.12     643  951.88   682.5  977.74     702  984.15     741 1009.63
#Mann= 3 , 0 , 0
       0     .08       0     628    .045       0     643     .08       0
#XS Ineff= 2 , 0
          595.22  956.84
Permanent Ineff=
       F       F
Bank Sta=628,643
XS Rating Curve= 0 ,0
Exp/Cntr=0.3,0.1

Type RM Length L Ch R = 1 ,12203.6 ,148.9,149.5,150
XS GIS Cut Line= 2
     1721232.924      332874.049     1721187.293      332485.565
#Sta/Elev= 27
       0   957.6     9.8  957.36    19.6  957.33      88   955.5    97.8  955.45
   156.5  954.12   166.2  953.95     176  953.92   195.6  954.04   205.4  953.72
   215.1  952.25   224.9  949.35   234.7  947.15   238.4  947.15   244.5  947.15
   253.4  947.58   254.2  947.62     264  950.07   283.6  957.62   322.7  971.07
   332.5  974.72   342.3  976.97     352  979.06   361.8  983.36   371.6  987.93
   381.4  992.79   391.2  997.88
#Mann= 3 , 0 , 0
       0     .08       0   238.4    .045       0   253.4     .08       0
Bank Sta=238.4,253.4
XS Rating Curve= 0 ,0
Exp/Cntr=0.3,0.1

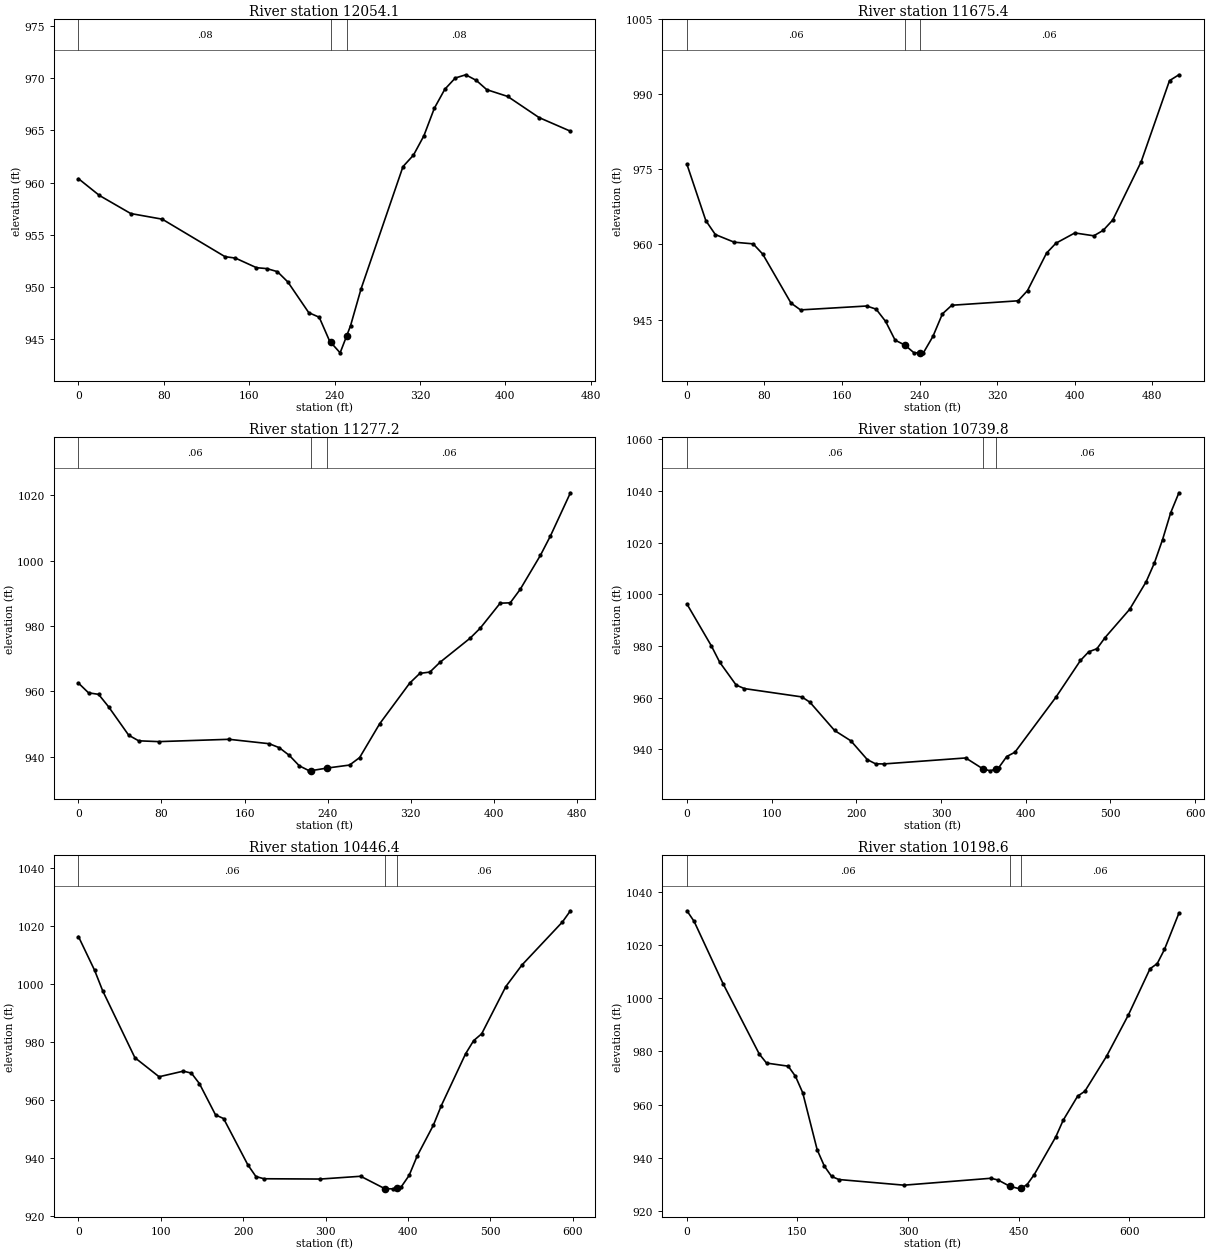
Type RM Length L Ch R = 1 ,12054.1 ,388,378.7,369.5
XS GIS Cut Line= 2
     1721374.977      332854.802     1721332.522      332395.731
#Sta/Elev= 30
       0  960.37    19.6  958.76      49  957.02    78.5  956.48   137.3  952.88
   147.1  952.74   166.8  951.82   176.6  951.73   186.4  951.44   196.2  950.45
   215.8   947.5   225.6  947.06   235.4  944.76   236.3  944.66   245.2  943.64
   251.3  945.26     255  946.26   264.8  949.78   304.1  961.53   313.9  962.63
   323.7  964.49   333.5  967.14   343.3  968.96   353.1  970.04   362.9  970.35
   372.8  969.81   382.6  968.92   402.2  968.27   431.6  966.24     461  964.93
#Mann= 3 , 0 , 0
       0     .08       0   236.3    .045       0   251.3     .08       0
Bank Sta=236.3,251.3
XS Rating Curve= 0 ,0
Exp/Cntr=0.3,0.1

Type RM Length L Ch R = 1 ,11675.4 ,384.7,398.2,411.7
XS GIS Cut Line= 2
     1721831.479      332767.262     1721588.101      332321.779
#Sta/Elev= 30
       0  976.02    19.5  964.76    29.3  961.98    48.8  960.45    68.3  960.12
    78.1   958.1   107.4  948.28   117.2  946.92   185.5   947.7   195.2  947.07
     205  944.62   214.8  940.87   225.1  939.87   234.3  938.34   240.1  938.35
     244  938.36   253.8  941.62   263.6  946.13   273.3  947.85   341.7  948.74
   351.4  950.78     371  958.26   380.7  960.25   400.2   962.3   419.8  961.73
   429.5  962.82   439.3  964.88   468.6   976.5   497.9  992.74   507.6  993.91
#Mann= 3 , 0 , 0
       0     .06       0   225.1    .045       0   240.1     .06       0
Bank Sta=225.1,240.1
XS Rating Curve= 0 ,0
Exp/Cntr=0.3,0.1

Type RM Length L Ch R = 1 ,11277.2 ,552.8,537.3,521.9
XS GIS Cut Line= 2
     1722062.407      332687.422     1722107.177      332215.526
#Sta/Elev= 30
       0   962.5     9.7  959.52    19.4  959.05      29  955.26    48.4  946.54
      58  944.82    77.4  944.57   145.1  945.28   183.8  943.93   193.5  942.71
   203.2  940.34   212.8  937.15   222.5  935.62   224.3  935.68   239.3  936.46
   261.2  937.39   270.9  939.68   290.2  950.03   319.2  962.51   328.9  965.47
   338.6  965.88   348.3  968.86   377.3  976.24     387  979.29   406.3  986.98
     416  987.09   425.6  991.21     445 1001.59   454.7 1007.55     474  1020.8
#Mann= 3 , 0 , 0
       0     .06       0   224.3    .045       0   239.3     .06       0
Bank Sta=224.3,239.3
XS Rating Curve= 0 ,0
Exp/Cntr=0.3,0.1

Type RM Length L Ch R = 1 ,10739.8 ,293.8,293.4,293
XS GIS Cut Line= 2
     1722755.183      332548.621     1722435.577      332063.517
#Sta/Elev= 30
       0  996.28      29  979.99    38.7  973.75    58.1  964.92    67.8  963.55
   135.6  960.33   145.2  958.28   174.3  947.34   193.6  943.32     213  936.05
   222.7  934.43   232.4  934.38   329.2   936.7   349.4  932.49   358.2  931.71
   364.4  932.41   367.9  932.82   377.6  937.25   387.3  938.92   435.7  960.22
   464.7  974.45   474.4  977.78   484.1  978.98   493.8  983.32   522.8  994.26
   542.2 1004.89   551.9 1012.12   561.6 1021.21   571.2 1031.61   580.9 1039.34
#Mann= 3 , 0 , 0
       0     .06       0   349.4    .045       0   364.4     .06       0
Bank Sta=349.4,364.4
XS Rating Curve= 0 ,0
Exp/Cntr=0.3,0.1

Type RM Length L Ch R = 1 ,10446.4 ,249,247.8,246.6
XS GIS Cut Line= 2
      1723015.86      332400.133     1722678.649      331907.283
#Sta/Elev= 30
       0 1016.43    19.6 1004.79    29.4  997.73    68.5  974.63    97.9  968.05
   127.3  969.99   137.1   969.3   146.8   965.7   166.4  954.89   176.2  953.62
   205.6  937.66   215.4  933.62   225.2  932.85   293.7  932.75   342.6  933.71
   372.1   929.4   381.8  929.37   387.1   929.7   391.6  929.97   401.4     934
   411.2  940.73   430.8  951.32   440.5   958.1   469.9  975.96   479.7  980.51
   489.5  982.89   518.8  999.19   538.4 1006.63   587.4 1021.44   597.2 1025.33
#Mann= 3 , 0 , 0
       0     .06       0   372.1    .045       0   387.1     .06       0
Bank Sta=372.1,387.1
XS Rating Curve= 0 ,0
Exp/Cntr=0.3,0.1

Type RM Length L Ch R = 1 ,10198.6 ,560.2,563.9,567.7
XS GIS Cut Line= 2
     1723258.751      332278.935     1722852.354      331749.375
#Sta/Elev= 30
       0    1033     9.8 1028.98    49.1 1005.49    98.2  979.01     108  975.63
   137.4  974.46   147.2  970.67   157.1  964.45   176.7  942.98   186.5  936.78
   196.3  932.92   206.2  931.76   294.5  929.63   412.3  932.23   422.1  931.59
   437.7  929.26   451.6  928.25   452.7  928.43   461.4  929.82   471.2  933.61
   500.6  947.91   510.5   954.1   530.1  963.17   539.9  965.01   569.4  978.23
   598.8  993.67   628.3 1011.15   638.1 1013.11   647.9 1018.44   667.5  1032.1
#Mann= 3 , 0 , 0
       0     .06       0   437.7    .045       0   452.7     .06       0
Bank Sta=437.7,452.7
XS Rating Curve= 0 ,0
Exp/Cntr=0.3,0.1

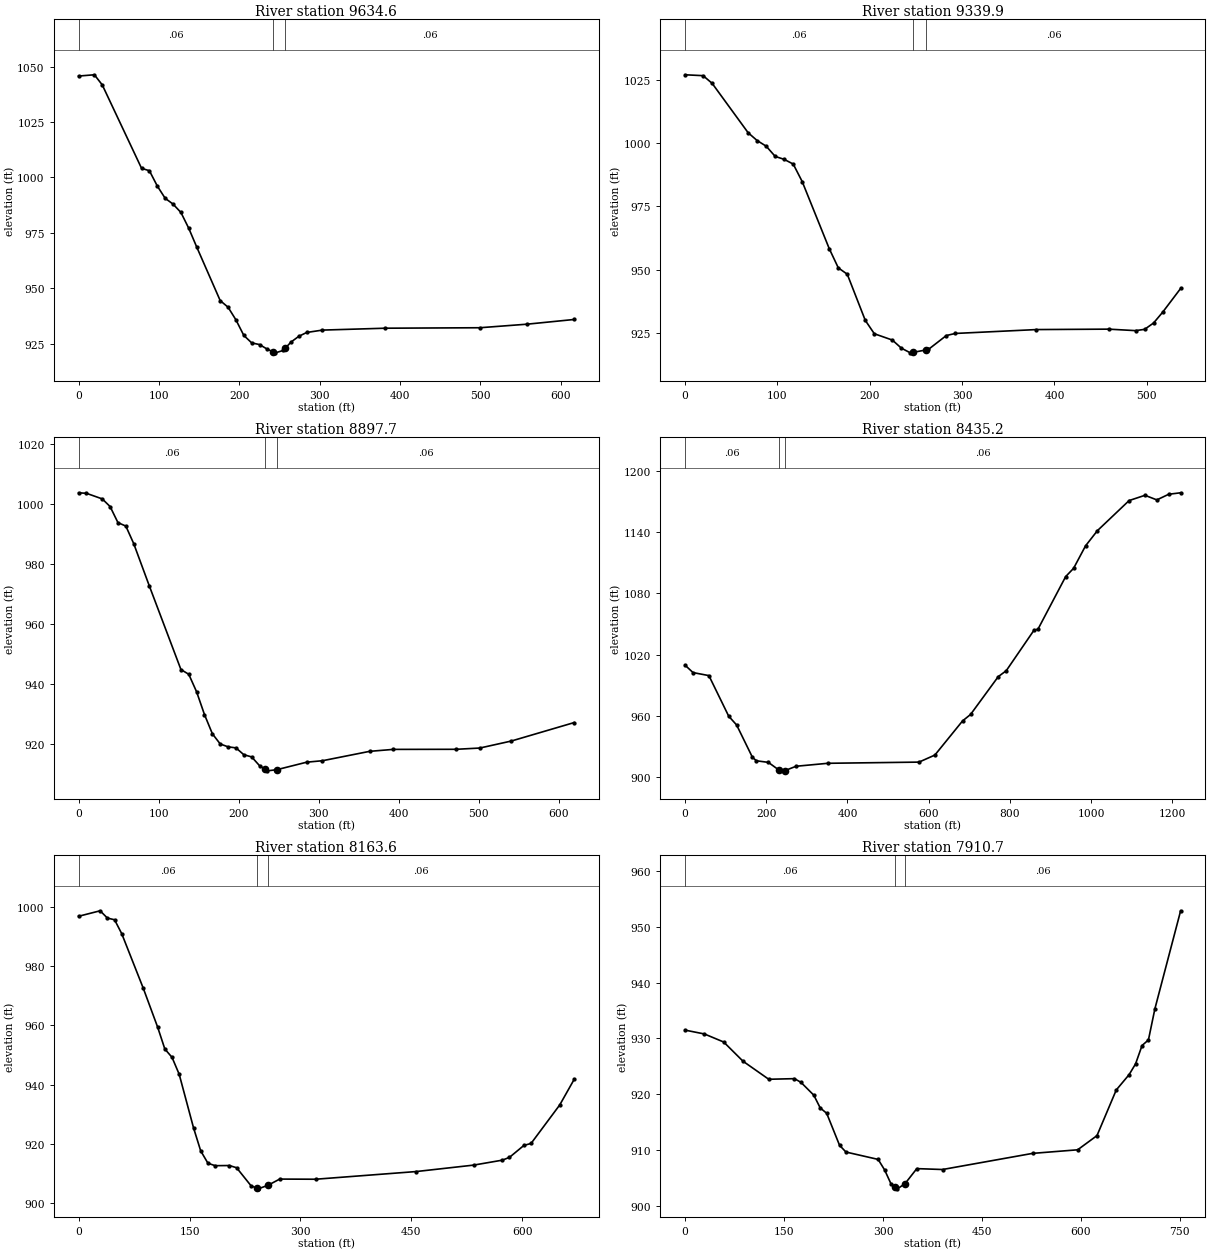
Type RM Length L Ch R = 1 ,9634.6  ,295.2,294.7,294.3
XS GIS Cut Line= 2
     1723620.562      331977.527     1723329.834      331433.564
#Sta/Elev= 30
       0 1045.76    19.6 1046.33    29.4 1041.77    78.3 1004.16    88.1 1003.04
    97.9  996.16   107.7  990.62   117.5  988.01   127.3  984.24   137.1  977.07
   146.8  968.79   176.2  944.48     186  941.49   195.8  935.78   205.6  928.77
   215.4   925.4   225.2  924.64     235  922.52   242.3  921.31   244.8  920.91
   254.5  921.97   257.3  923.04   264.3  925.75   274.1  928.38   283.9   930.1
   303.5  931.17   381.8  932.02   499.3  932.23     558  933.83   616.8  935.96
#Mann= 3 , 0 , 0
       0     .06       0   242.3    .045       0   257.3     .06       0
Bank Sta=242.3,257.3
XS Rating Curve= 0 ,0
Exp/Cntr=0.3,0.1

Type RM Length L Ch R = 1 ,9339.9  ,429,442.2,455.5
XS GIS Cut Line= 2
     1723878.219      331824.909     1723615.085      331357.243
#Sta/Elev= 30
       0    1027    19.5 1026.65    29.3 1023.61    68.3 1004.09      78 1001.03
    87.8   998.8    97.6  994.75   107.3  993.59   117.1  991.73   126.8  984.82
   156.1  958.32   165.9  950.74   175.6  948.24   195.1  930.01   204.9  924.72
   224.4  922.23   234.2  919.03   243.9  917.18   246.4  917.34   261.4  918.36
   263.4  918.51   282.9  924.02   292.7  924.84   380.5  926.37   458.6  926.54
   487.8  925.95   497.6  926.46   507.3  928.97   517.1  933.21   536.6  942.61
#Mann= 3 , 0 , 0
       0     .06       0   246.4    .045       0   261.4     .06       0
Bank Sta=246.4,261.4
XS Rating Curve= 0 ,0
Exp/Cntr=0.3,0.1

Type RM Length L Ch R = 1 ,8897.7  ,455.8,462.4,469
XS GIS Cut Line= 2
     1724154.758      331752.693     1724199.392      331135.184
#Sta/Elev= 30
       0 1003.65     9.8 1003.47    29.5 1001.61    39.3  999.06    49.1  993.71
      59  992.54    68.8  986.71    88.4  972.54   127.8  944.73   137.6  943.14
   147.4   937.3   157.2  929.73   167.1  923.31   176.9  919.92   186.7  918.96
   196.6  918.61   206.4  916.33   216.2   915.6     226  912.68   232.6  911.53
   235.9  910.96   247.6  911.34     285  913.85   304.6  914.33   363.6  917.46
   393.1  918.11   471.7  918.14   501.2  918.56   540.5  920.89   619.1  927.05
#Mann= 3 , 0 , 0
       0     .06       0   232.6    .045       0   247.6     .06       0
Bank Sta=232.6,247.6
XS Rating Curve= 0 ,0
Exp/Cntr=0.3,0.1

Type RM Length L Ch R = 1 ,8435.2  ,275.8,271.6,267.4
XS GIS Cut Line= 2
     1724511.806      331914.095     1724947.443      330773.866
#Sta/Elev= 30
       0 1009.51    19.5  1002.3    58.6  999.34   107.4   959.6   126.9  950.99
     166  919.22   175.8  915.92   205.1  914.37     231  906.89   244.1  906.08
     246  906.33   273.4  910.56   351.5  913.47   576.1  914.63   615.2  921.52
   683.5  954.99   703.1  961.26   771.4  998.34     791  1004.1   859.3 1043.73
   869.1 1044.72   937.4 1096.28     957 1104.43   986.3 1126.35  1015.6 1141.27
  1093.7 1170.75  1132.7 1175.89    1162 1171.39  1191.3 1176.92  1220.6 1178.36
#Mann= 3 , 0 , 0
       0     .06       0     231    .045       0     246     .06       0
Bank Sta=231,246
XS Rating Curve= 0 ,0
Exp/Cntr=0.3,0.1

Type RM Length L Ch R = 1 ,8163.6  ,256.2,252.9,249.7
XS GIS Cut Line= 2
     1724808.382      332026.472     1724928.069      331366.961
#Sta/Elev= 30
       0  996.79    29.1  998.64    38.9  996.18    48.6  995.61    58.3  990.92
    87.4  972.54   106.9  959.39   116.6  952.03   126.3  949.23     136  943.53
   155.4  925.47   165.1  917.69   174.9  913.52   184.6  912.69     204  912.74
   213.7  911.99   233.1  905.95     241  905.09   242.9  904.88     256  906.07
     272  908.17   320.6  908.12   456.6  910.71   534.3  912.88   573.1  914.55
   582.8   915.5   602.3  919.52     612  920.19   650.8  933.18   670.3   941.8
#Mann= 3 , 0 , 0
       0     .06       0     241    .045       0     256     .06       0
Bank Sta=241,256
XS Rating Curve= 0 ,0
Exp/Cntr=0.3,0.1

Type RM Length L Ch R = 1 ,7910.7  ,764.1,761,757.9
XS GIS Cut Line= 2
     1725092.004      332136.336     1725117.903      331385.711
#Sta/Elev= 30
       0  931.49    29.3   930.8    58.5  929.36    87.8  925.92   126.8  922.69
   165.8   922.8   175.6  922.14   195.1  919.84   204.8  917.56   214.6   916.6
   234.1  910.87   243.8  909.66   292.6  908.34   302.4  906.46   312.1  903.96
   318.5  903.38   321.9  903.07   333.5  904.02   351.2  906.69   390.2  906.53
   526.7  909.42     595  910.06   624.3   912.6   653.5  920.77     673  923.52
   682.8  925.45   692.6  928.73   702.3  929.74   712.1  935.32   751.1  952.86
#Mann= 3 , 0 , 0
       0     .06       0   318.5    .045       0   333.5     .06       0
Bank Sta=318.5,333.5
XS Rating Curve= 0 ,0
Exp/Cntr=0.3,0.1