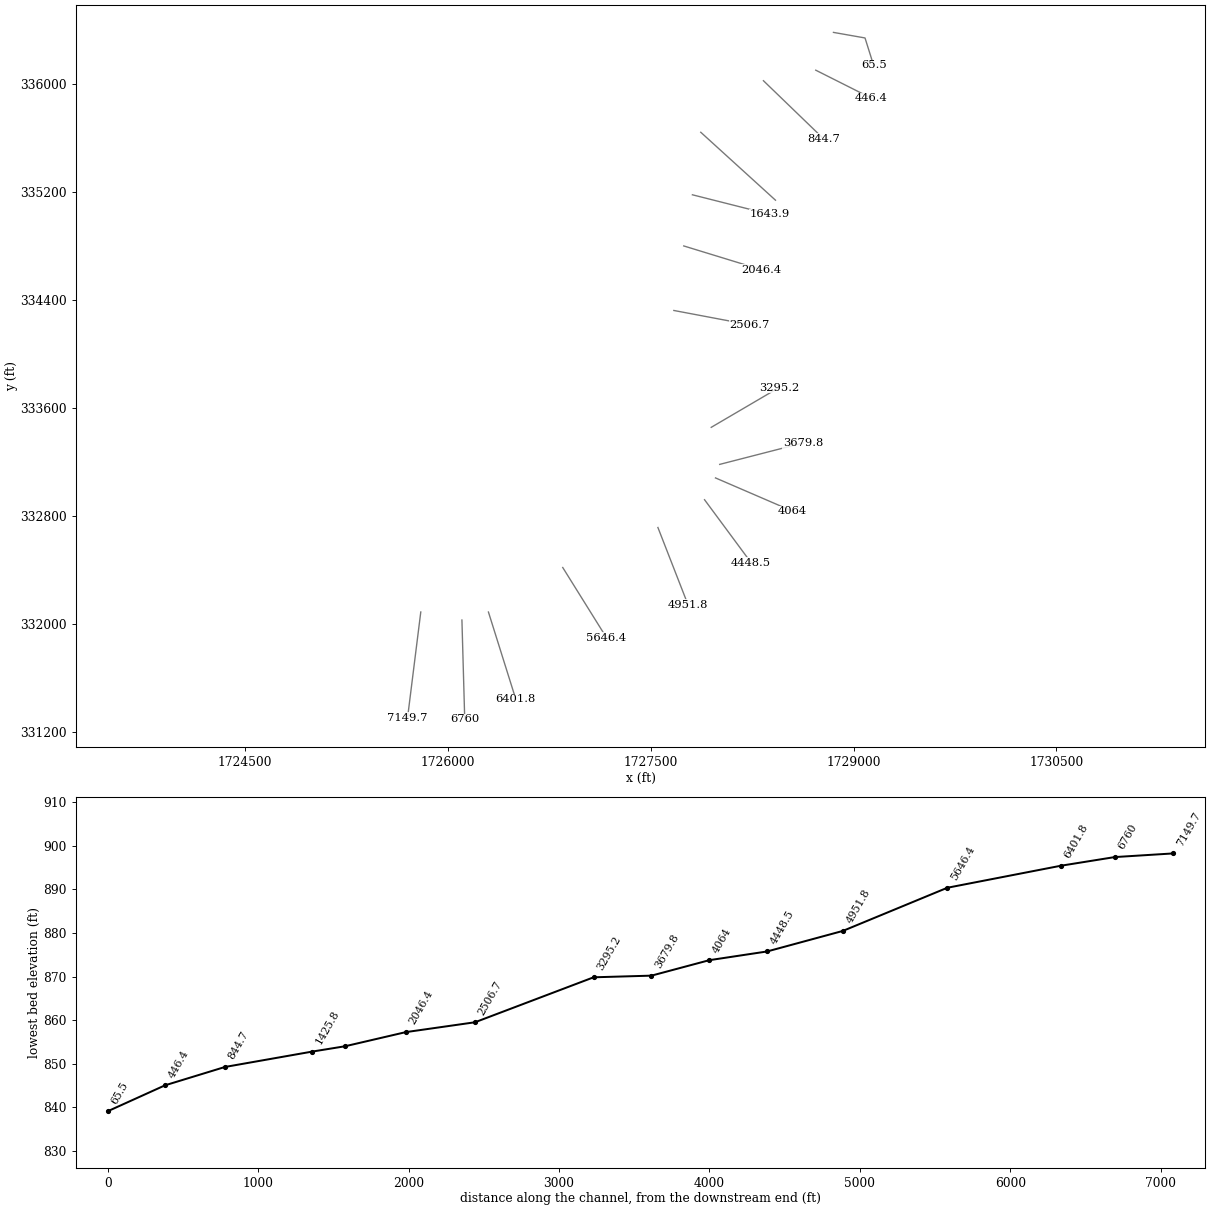
HEC-RAS study BEECHCRK.prj: BEECHCRK

--- BEECHCRK.g01 (geometry) --- (continued)

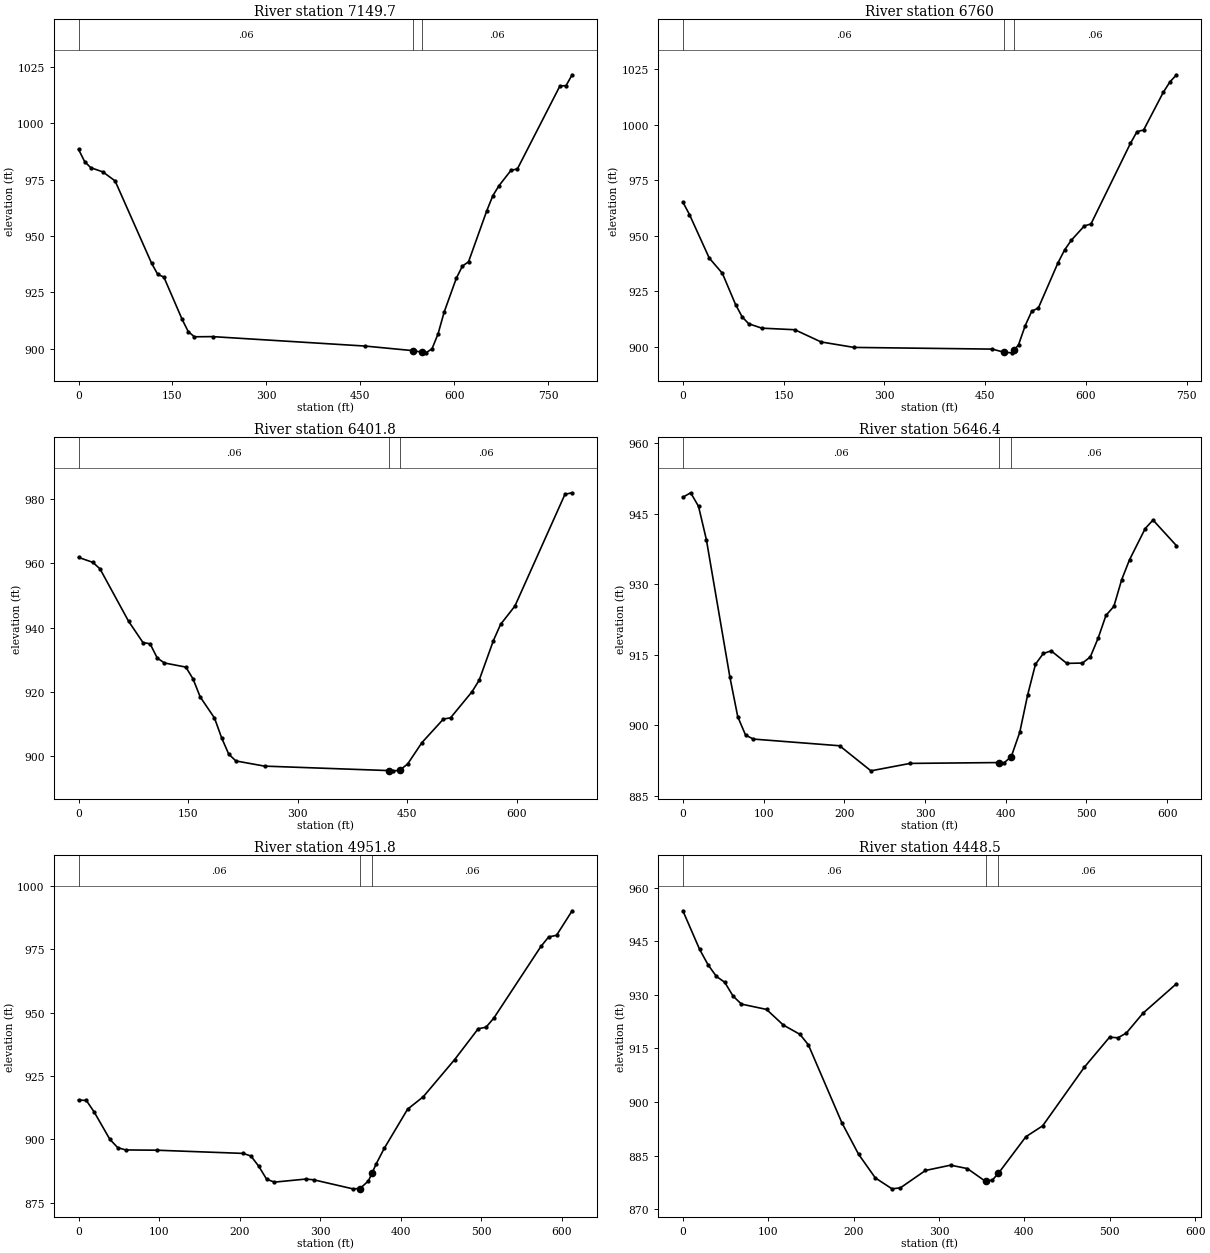
Type RM Length L Ch R = 1 ,7149.7  ,386.3,389.8,393.2
XS GIS Cut Line= 2
     1725798.351      332091.286     1725700.543      331308.907
#Sta/Elev= 30
       0  988.41     9.7  983.02    19.5  980.28    38.9  978.41    58.4  974.42
   116.8  937.86   126.5     933   136.3  931.79   165.5  913.03   175.2  907.64
     185  905.32   214.2  905.39   457.5  901.21   533.6  899.19   548.6  898.51
   554.8   898.2   564.6  899.95   574.3   906.6     584  916.22   603.5  931.28
   613.2  936.65     623  938.57   652.2  961.24   661.9   967.9   671.7  972.33
   691.1   979.2   700.9  979.66     769 1016.52   778.7 1016.64   788.5 1021.47
#Mann= 3 , 0 , 0
       0     .06       0   533.6    .045       0   548.6     .06       0
Bank Sta=533.6,548.6
XS Rating Curve= 0 ,0
Exp/Cntr=0.3,0.1

Type RM Length L Ch R = 1 ,6760    ,352.3,358.2,363.9
XS GIS Cut Line= 2
     1726102.707      332031.754     1726123.474      331297.394
#Sta/Elev= 30
       0  965.15     9.8  959.58    39.2  940.02    58.8  933.12    78.4   919.1
    88.2  913.55      98  910.43   117.5  908.46   166.5  907.76   205.7  902.26
   254.7   899.8   460.4  899.04   478.1  897.62   489.8  897.36   493.1  898.61
   499.6  901.03   509.4  909.55   519.2   916.1     529  917.52   558.3  937.88
   568.1  943.65   577.9  947.94   597.5  954.46   607.3  955.32   666.1  991.61
   675.9  996.88   685.7  997.59   715.1 1014.64   724.9 1019.25   734.6 1022.44
#Mann= 3 , 0 , 0
       0     .06       0   478.1    .045       0   493.1     .06       0
Bank Sta=478.1,493.1
XS Rating Curve= 0 ,0
Exp/Cntr=0.3,0.1

Type RM Length L Ch R = 1 ,6401.8  ,749.3,755.4,761.7
XS GIS Cut Line= 2
     1726298.821       332090.92     1726501.349      331445.952
#Sta/Elev= 30
       0  961.85    19.6  960.29    29.4  958.27    68.6  941.93    88.2  935.34
      98  934.93   107.8  930.51   117.6  928.97     147  927.68   156.8  924.01
   166.6   918.4   186.2  911.82     196  905.64   205.7  900.58   215.5  898.46
   254.7  896.85   424.6  895.46   431.1  895.38   439.6  895.53   450.7  897.51
   470.3  904.18   499.7   911.5   509.5  911.89   538.9  920.02   548.6  923.57
   568.2  935.96     578  940.99   597.6  946.68   666.2   981.5     676  981.96
#Mann= 3 , 0 , 0
       0     .06       0   424.6    .045       0   439.6     .06       0
Bank Sta=424.6,439.6
XS Rating Curve= 0 ,0
Exp/Cntr=0.3,0.1

Type RM Length L Ch R = 1 ,5646.4  ,698.8,694.6,690.4
XS GIS Cut Line= 2
     1726848.516      332420.201     1727172.133      331901.212
#Sta/Elev= 30
       0  948.49     9.7  949.43    19.4  946.54    29.1  939.48    58.2   910.3
      68  901.83    77.7  897.92    87.4  897.08   194.2  895.66     233  890.33
   281.5  891.91   391.9  892.09     398  892.04   406.9  893.35   417.4  898.52
   427.2  906.48   436.9     913   446.6  915.27   456.3  915.83   475.7  913.17
   495.1  913.24   504.8  914.53   514.5  918.52   524.2  923.36     534  925.28
   543.7  930.96   553.4  935.19   572.8  941.81   582.5  943.64   611.6  938.18
#Mann= 3 , 0 , 0
       0     .06       0   391.9    .045       0   406.9     .06       0
Bank Sta=391.9,406.9
XS Rating Curve= 0 ,0
Exp/Cntr=0.3,0.1

Type RM Length L Ch R = 1 ,4951.8  ,497.3,503.3,509.3
XS GIS Cut Line= 2
     1727552.511      332716.264     1727774.955      332145.428
#Sta/Elev= 30
       0  915.54     9.7  915.35    19.4   910.8    38.9  899.98    48.6  896.74
    58.4  895.81    97.2   895.7   204.2  894.44   213.9  893.42   223.7  889.35
   233.4  884.25   243.1  883.09     282   884.3   291.7  884.02   340.4  880.44
   349.3  880.55   359.8  883.58   364.3  886.71   369.5  890.35   379.3  896.38
   408.4  911.91   427.9  916.84   466.8  931.51     496  943.68   505.7  944.28
   515.4   947.9   573.8  976.18   583.5  979.97   593.2  980.59   612.6  990.29
#Mann= 3 , 0 , 0
       0     .06       0   349.3    .045       0   364.3     .06       0
Bank Sta=349.3,364.3
XS Rating Curve= 0 ,0
Exp/Cntr=0.3,0.1

Type RM Length L Ch R = 1 ,4448.5  ,372.5,384.5,396.5
XS GIS Cut Line= 2
     1727897.391      332921.733     1728241.213      332456.903
#Sta/Elev= 30
       0  953.51    19.6  942.72    29.4  938.45    39.2  935.16      49  933.52
    58.8  929.65    68.6  927.41      98  925.92   117.6  921.56   137.2  918.94
     147  916.01   186.2  894.24   205.8  885.42   225.4   878.8     245  875.74
   254.8  876.02   284.2  880.88   313.6  882.36   333.2  881.41   354.5  877.83
   362.6  878.22   369.5  880.05   401.8  890.32   421.4  893.35   470.4   909.8
   499.8  918.15   509.6  917.99   519.4   919.3     539  924.87   578.2  933.11
#Mann= 3 , 0 , 0
       0     .06       0   354.5    .045       0   369.5     .06       0
Bank Sta=354.5,369.5
XS Rating Curve= 0 ,0
Exp/Cntr=0.3,0.1

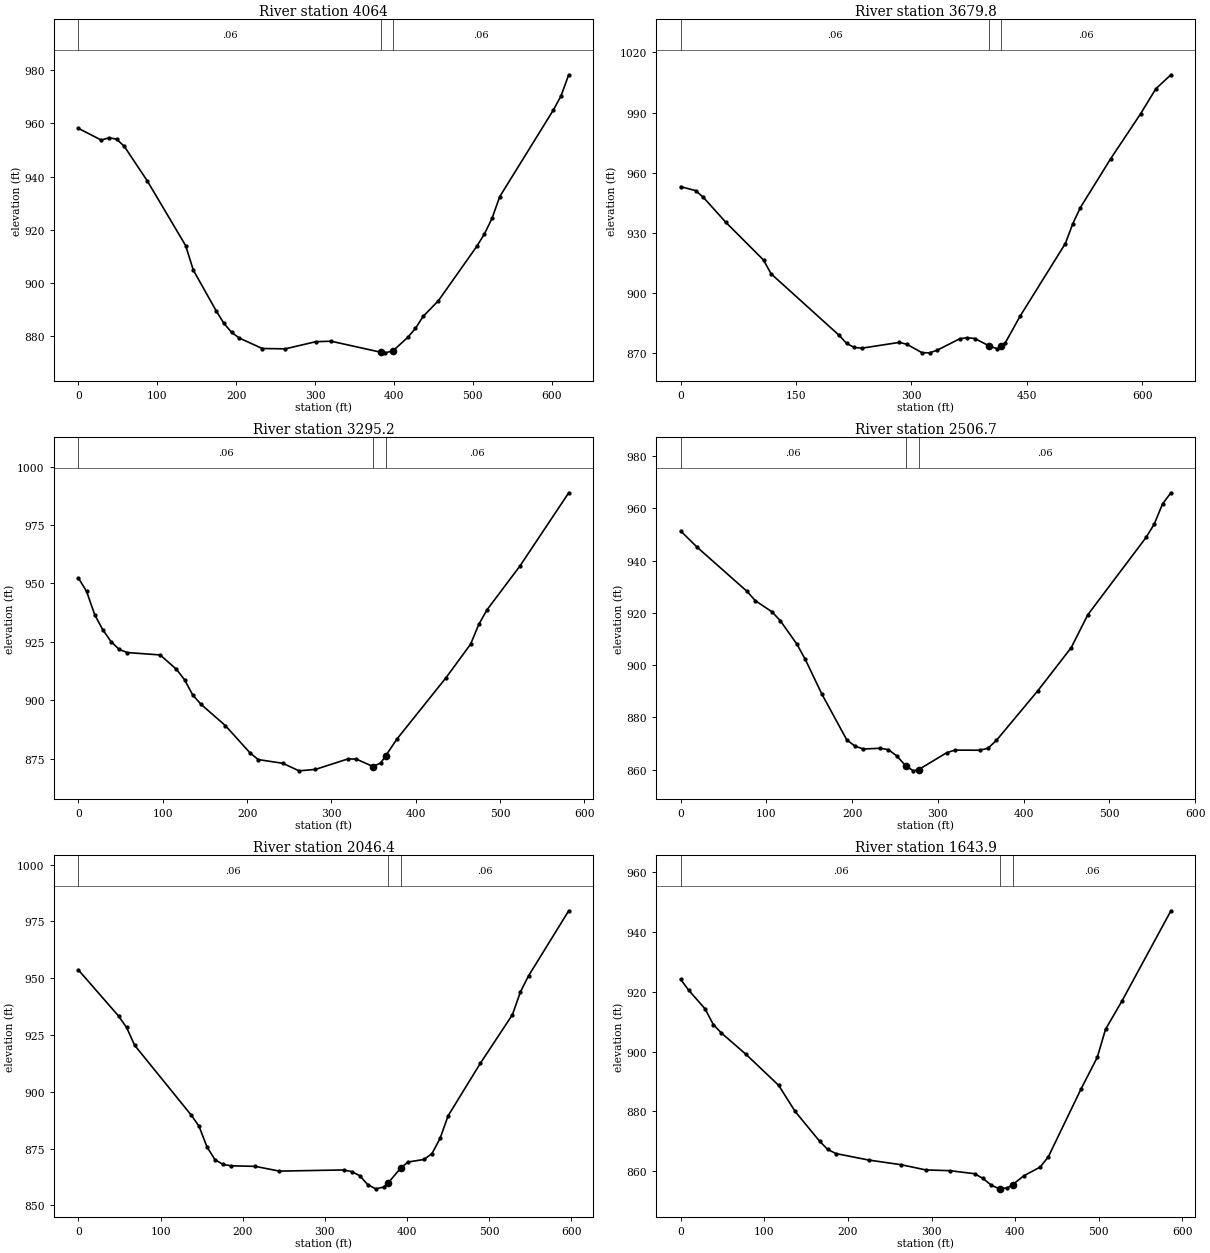
Type RM Length L Ch R = 1 ,4064    ,369.2,384.2,399.2
XS GIS Cut Line= 2
     1727978.392       333083.02     1728549.026      332836.686
#Sta/Elev= 30
       0  958.13    29.1   953.7    38.8  954.59    48.6  954.05    58.3  951.32
    87.4  938.34     136  914.04   145.7  904.82   174.8  889.46   184.5  884.81
   194.2  881.45   203.9  879.31   233.1  875.37   262.2  875.24   301.1  877.94
   320.5   878.1   383.6  873.95   388.5  873.74   398.6  874.44   417.6   879.6
   427.3  882.96     437  887.44   456.4  893.36     505  913.78   514.7  918.44
   524.4  924.37   534.1  932.46   602.1  965.04   611.8  970.36   621.5  978.26
#Mann= 3 , 0 , 0
       0     .06       0   383.6    .045       0   398.6     .06       0
Bank Sta=383.6,398.6
XS Rating Curve= 0 ,0
Exp/Cntr=0.3,0.1

Type RM Length L Ch R = 1 ,3679.8  ,378.3,384.6,390.9
XS GIS Cut Line= 2
     1728009.593      333183.132     1728626.697      333341.863
#Sta/Elev= 30
       0  953.08    19.6   951.1    29.4  947.83    58.8   935.3   107.8  916.47
   117.6  909.62   205.9  878.99   215.7  874.92   225.5  872.92   235.3  872.52
   284.3  875.41   294.1  874.47   313.7  870.28   323.5   870.2   333.3  871.48
   362.7   877.2   372.5  877.76   382.3  877.34     401  873.66   411.7   872.2
     416  873.37   421.5  874.88   441.1  888.42     500   924.7   509.8   934.7
   519.6  942.68   558.8  966.94     598  989.54   617.6  1001.9   637.2 1008.87
#Mann= 3 , 0 , 0
       0     .06       0     401    .045       0     416     .06       0
Bank Sta=401,416
XS Rating Curve= 0 ,0
Exp/Cntr=0.3,0.1

Type RM Length L Ch R = 1 ,3295.2  ,804.8,788.6,772.4
XS GIS Cut Line= 2
     1727946.837      333457.214     1728448.325      333751.201
#Sta/Elev= 30
       0  952.31     9.7  946.62    19.4  936.57    29.1  930.09    38.8  925.08
    48.4  921.75    58.1  920.42    96.9   919.4   116.3  913.25     126  908.72
   135.6  902.25   145.3  898.31   174.4  889.14   203.5  877.49   213.2  874.63
   242.2  873.06   261.6  869.82     281  870.43   319.7  874.93   329.4  874.85
   349.4  871.66   358.5  873.22   364.4   876.3   377.8  883.48     436  909.73
     465  924.01   474.7  932.48   484.4  938.69   523.2   957.3   581.3  988.77
#Mann= 3 , 0 , 0
       0     .06       0   349.4    .045       0   364.4     .06       0
Bank Sta=349.4,364.4
XS Rating Curve= 0 ,0
Exp/Cntr=0.3,0.1

Type RM Length L Ch R = 1 ,2506.7  ,462.7,460.3,457.8
XS GIS Cut Line= 2
     1727670.435      334321.659     1728232.315      334215.497
#Sta/Elev= 30
       0  951.38    19.4  945.11    77.5  928.22    87.2  924.64   106.6   920.4
   116.3  916.99   135.7  907.99   145.4  902.19   164.8  888.89   193.8  871.38
   203.5  868.96   213.2  867.88   232.6  868.16   242.3  867.64     252  865.26
   262.6  861.44   271.4  859.52   277.6  859.99   310.1  866.41   319.8  867.46
   348.9  867.41   358.6   868.2   368.3  871.17   416.8  890.27   455.5  906.67
   474.9  919.28   542.8  948.87   552.4  954.02   562.1  961.75   571.8  965.97
#Mann= 3 , 0 , 0
       0     .06       0   262.6    .045       0   277.6     .06       0
Bank Sta=262.6,277.6
XS Rating Curve= 0 ,0
Exp/Cntr=0.3,0.1

Type RM Length L Ch R = 1 ,2046.4  ,401.4,402.5,403.6
XS GIS Cut Line= 2
     1727743.638      334799.022     1728314.342      334624.188
#Sta/Elev= 30
       0  953.68    48.9  933.38    58.7  928.33    68.5  920.48     137   889.9
   146.8  884.89   156.6  875.69   166.3   870.1   176.1  868.01   185.9   867.4
   215.3  867.16   244.6  865.07   322.9  865.58   332.7  864.84   342.5  863.06
   352.3  859.08     362  857.26   371.8  858.04   377.2  859.91   392.2  866.33
   401.2  869.07   420.8   870.2   430.5   872.8   440.3  879.48   450.1  889.43
   489.2  912.48   528.4  933.96   538.2  944.08     548  951.08   596.9  979.72
#Mann= 3 , 0 , 0
       0     .06       0   377.2    .045       0   392.2     .06       0
Bank Sta=377.2,392.2
XS Rating Curve= 0 ,0
Exp/Cntr=0.3,0.1

Type RM Length L Ch R = 1 ,1643.9  ,229.3,218.2,207
XS GIS Cut Line= 2
     1727807.644      335177.435      1728375.89      335033.684
#Sta/Elev= 30
       0  924.19     9.8   920.5    29.3  914.28    39.1  909.04    48.8   906.2
    78.2  899.06   117.2   888.7   136.8     880   166.1     870   175.8  867.25
   185.6  865.85   224.7  863.68   263.8   862.1   293.1  860.37   322.4   860.1
   351.7  859.08   361.5   857.5   371.2  855.31     381  854.03   382.3  854.07
   390.8  854.37   397.3  855.48   410.3   858.4   429.8   861.3   439.6  864.73
   478.7  887.44   498.2  898.07     508  907.44   527.5  916.82   586.2  947.12
#Mann= 3 , 0 , 0
       0     .06       0   382.3    .045       0   397.3     .06       0
Bank Sta=382.3,397.3
XS Rating Curve= 0 ,0
Exp/Cntr=0.3,0.1

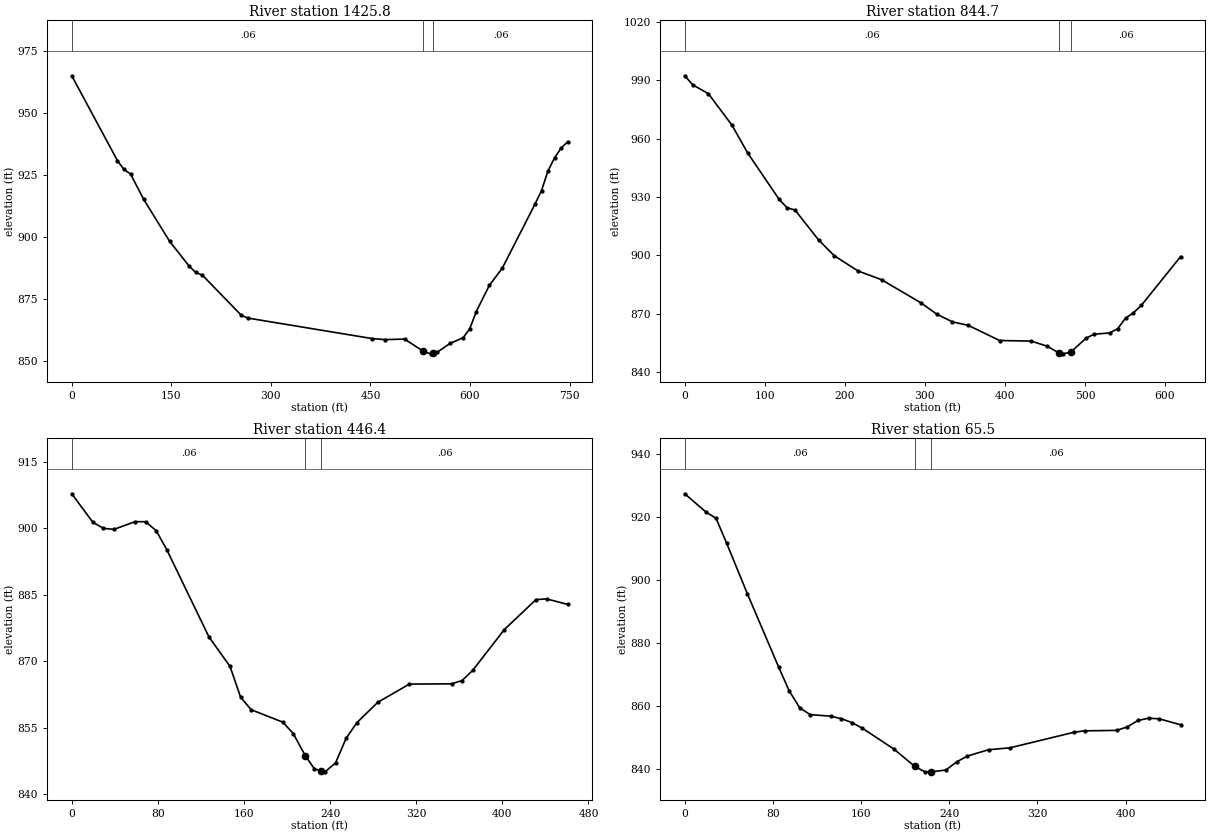
Type RM Length L Ch R = 1 ,1425.8  ,581.7,581.1,580.4
XS GIS Cut Line= 2
     1727869.457       335639.92      1728422.18      335137.442
#Sta/Elev= 30
       0  964.89    68.8  930.69    78.6  927.13    88.5  925.33   108.1  915.18
   147.4  898.18   176.9  888.14   186.8   885.6   196.6  884.57   255.6   868.3
   265.4  867.22   452.1  858.98   471.8  858.54   501.3  858.76   529.6  853.85
   540.6  852.81   544.6  853.07   550.4  853.44   570.1  857.04   589.7  859.33
   599.6  862.97   609.4  869.86     629  880.37   648.7  887.39   697.8  913.13
   707.7  918.62   717.5  926.58   727.3   931.8   737.2  935.78     747  938.23
#Mann= 3 , 0 , 0
       0     .06       0   529.6    .045       0   544.6     .06       0
Bank Sta=529.6,544.6
XS Rating Curve= 0 ,0
Exp/Cntr=0.3,0.1

Type RM Length L Ch R = 1 ,844.7   ,391.5,398.3,405.1
XS GIS Cut Line= 2
     1728333.104      336021.177     1728778.811      335590.904
#Sta/Elev= 30
       0  992.37     9.8  987.76    29.5  983.15      59  966.92    78.7  952.55
     118  928.71   127.8  924.44   137.7   923.3   167.2  907.86   186.8  899.77
   216.3  891.96   245.8  887.44     295  875.54   314.7  869.74   334.3  865.73
     354  863.97   393.3  856.14   432.7  855.84   452.3  853.29     467  849.87
     472  849.28     482  850.11   501.5  857.37   511.3  859.38     531  860.04
   540.8  862.19   550.7  867.68   560.5  870.37   570.3  874.18   619.5  899.33
#Mann= 3 , 0 , 0
       0     .06       0     467    .045       0     482     .06       0
Bank Sta=467,482
XS Rating Curve= 0 ,0
Exp/Cntr=0.3,0.1

Type RM Length L Ch R = 1 ,446.4   ,374.3,380.9,380.6
XS GIS Cut Line= 2
     1728720.019      336099.269     1729131.486      335892.198
#Sta/Elev= 30
       0  907.79    19.6  901.36    29.4     900    39.2  899.76    58.8  901.51
    68.6  901.48    78.4  899.47    88.2  895.21   127.4  875.52     147  868.86
   156.8  861.94   166.6  859.09     196  856.29   205.8  853.69   216.9  848.74
   225.4  845.74   231.9   845.3   235.2  845.08     245  847.07   254.8  852.61
   264.6  856.11   284.2  860.75   313.6  864.87   352.8  864.93   362.6  865.67
   372.4  867.96   401.8  877.16   431.2  883.92     441  884.09   460.6  882.84
#Mann= 3 , 0 , 0
       0     .06       0   216.9    .045       0   231.9     .06       0
Bank Sta=216.9,231.9
XS Rating Curve= 0 ,0
Exp/Cntr=0.3,0.1

Type RM Length L Ch R = 1 ,65.5    ,59.6,65.5,78.3
XS GIS Cut Line= 3
     1728851.106      336378.644     1729084.486      336337.535
     1729148.345      336134.354
#Sta/Elev= 30
       0  927.24      19  921.52    28.4  919.45    37.9  911.65    56.9  895.48
    85.3  872.24    94.8  864.77   104.3  859.42   113.8  857.28   132.7  856.76
   142.2  855.96   151.7  854.76   161.1  852.97   189.6   846.4   208.8  840.84
     218  839.14   223.8  839.15     237  839.72   246.6  842.25   256.3  844.12
   275.7  846.15   295.1  846.75   353.1  851.67   362.8  852.13   391.9  852.27
   401.6  853.38   411.2  855.41   420.9  856.14   430.6  855.94     450  854.05
#Mann= 3 , 0 , 0
       0     .06       0   208.8    .045       0   223.8     .06       0
Bank Sta=208.8,223.8
XS Rating Curve= 0 ,0
Exp/Cntr=0.3,0.1

Chan Stop Cuts=-1
Use User Specified Reach Order=0
Composite Channel Slope=5